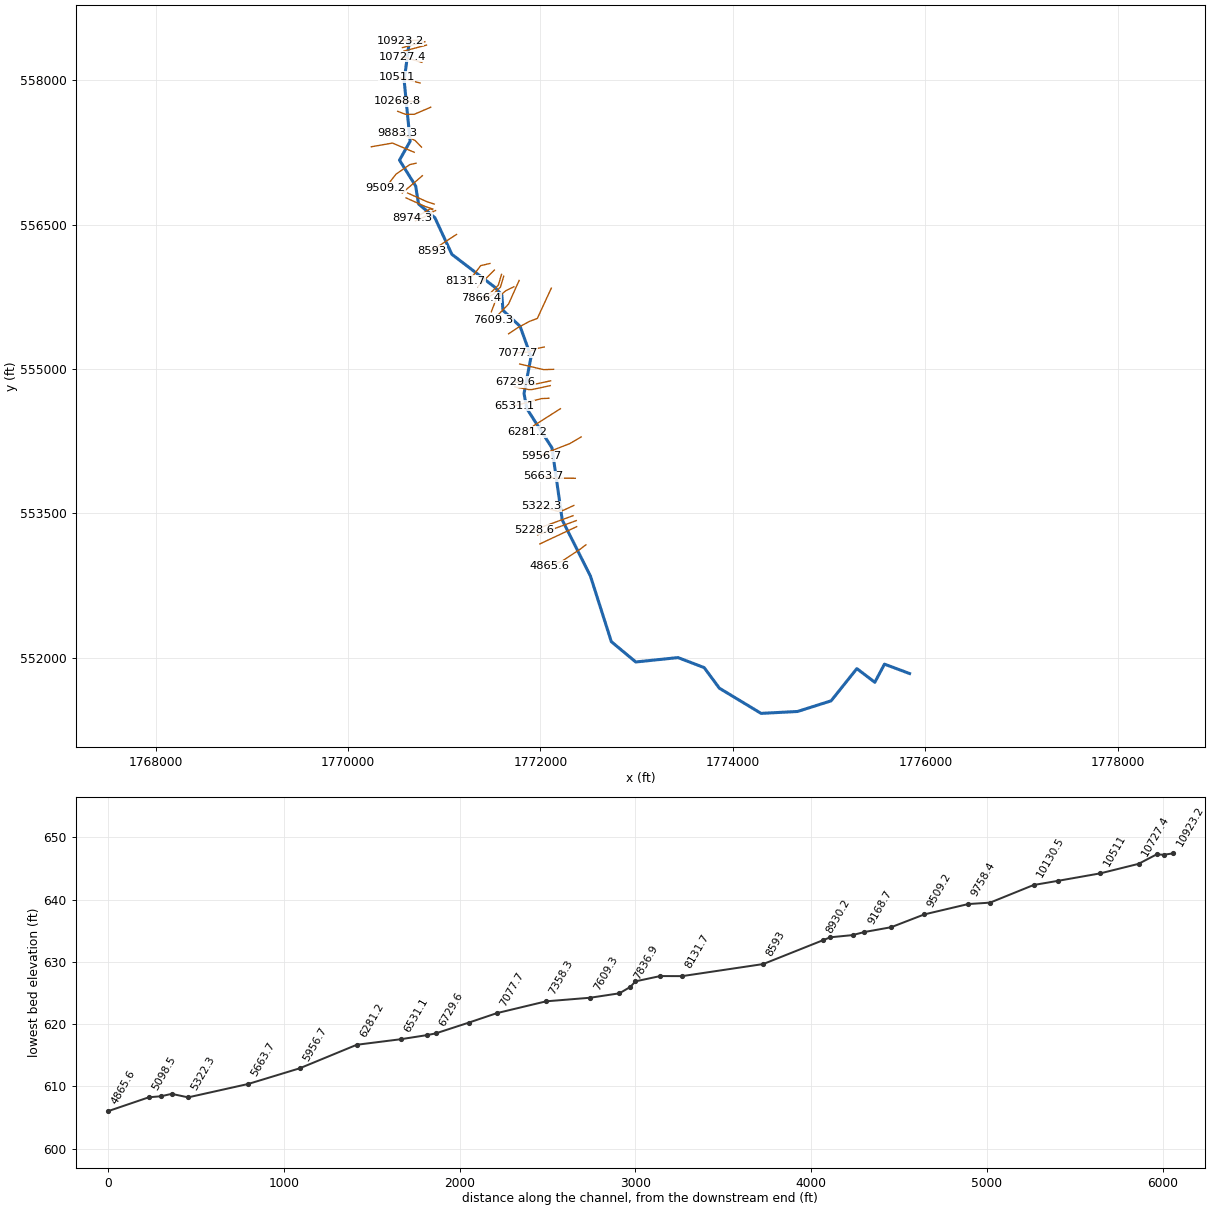
--- DERRICKCK.prj (project) ---

Proj Title=DERRICKCK
Current Plan=p01
Default Exp/Contr=0,0
English Units
Geom File=g01
Flow File=f01
Plan File=p01
BEGIN DESCRIPTION:
END DESCRIPTION:
DSS Export Rating Curves= 0
DSS Export Rating Curve Sorted= 0
DSS Export Volume Flow Curves= 0
DXF OffsetX= 0
DXF OffsetY= 0
DXF ScaleX= 0
DXF ScaleY= 0

--- DERRICKCK.p01 (plan) ---

Plan Title=Floodplain
Program Version=4.00
Geom File=g01
Flow File=f01
K Sum by GR=0
Std Step Tol=0.01
Critical Tol=0.01
Num of Std Step Trials=20
Max Error Tol=0.3
Flow Tol Ratio=0.001
Split Flow NTrial=30
Split Flow Tol=0.02
Split Flow Ratio=0.02
Log Output Level=0
Friction Slope Method=1
Unsteady Friction Slope Method=2
Unsteady Bridges Friction Slope Method=1
Global Log Level=0
CheckData=False
Run HTab=0
Run UNet=0
Run PostProcess=0
UNET Theta=0
UNET Theta Warmup=0
UNET ZTol=0
UNET ZSATol=0
UNET MxIter=0
UNET MaxInSteps=0
UNET DtIC=0
UNET DtMin=0
UNET MaxCRTS=0
UNET WFStab=0
UNET SFStab=0
UNET WFX=0
UNET SFX=0
UNET DSS MLevel=0
UNET DZMax Abort=0
UNET Convert EG Bridges=0
UNET Use Existing IB Tables=0
UNET Froude Limit=0
UNET Froude Power=0
Write IC File=0
Echo Input=False
Echo Output=False
Write Detailed=0

--- DERRICKCK.f01 (steady flow) ---

Flow Title=NFF Regression Equation
Program Version=4.10
Number of Profiles= 1
Profile Names=P100yr
River Rch & RM=DERRICKCK,Main            ,10923.2
895.7978
River Rch & RM=DERRICKCK,Main            ,9509.2
965.3159
River Rch & RM=DERRICKCK,Main            ,7358.3
1138.498
River Rch & RM=DERRICKCK,Main            ,6729.6
1164.481
River Rch & RM=DERRICKCK,Main            ,4865.6
1257.319
River Rch & RM=DERRICKCK,Main            ,3346
1317.946
River Rch & RM=DERRICKCK,Main            ,497.4
1413.897
Boundary for River Rch & Prof#=DERRICKCK,Main            , 1
Up Type= 0
Dn Type= 3
Dn Slope=0.002
DSS Import GetInterval= 0
DSS Import GetPeak= 0
DSS Import FillOption= 0

--- DERRICKCK.g01 (geometry) ---

Geom Title=USGS 10m DEM
Program Version=4.10

River Reach=DERRICKCK       ,Main
Reach XY= 30
     1770641.399      558434.735     1770583.158      557996.721
     1770645.756      557365.989     1770534.645      557169.808
     1770702.613      556901.145     1770733.024      556714.323
     1770901.971      556572.794     1771078.915      556191.509
     1771522.926      555851.666     1771598.447      555769.634
     1771610.166      555609.478     1771788.551      555442.811
     1771901.832      555126.405     1771828.916      554744.895
     1771858.863      554587.343      1772119.28      554181.093
     1772226.079      553431.988     1772519.266      552849.343
     1772736.468      552168.072     1772990.374      551957.134
     1773429.176      552002.707     1773701.311      551898.541
     1773858.864      551684.999     1774292.457       551423.28
     1774671.364      551442.812     1775020.322      551553.488
     1775287.928      551888.151     1775474.749      551746.197
     1775574.908      551934.505     1775835.792      551837.215

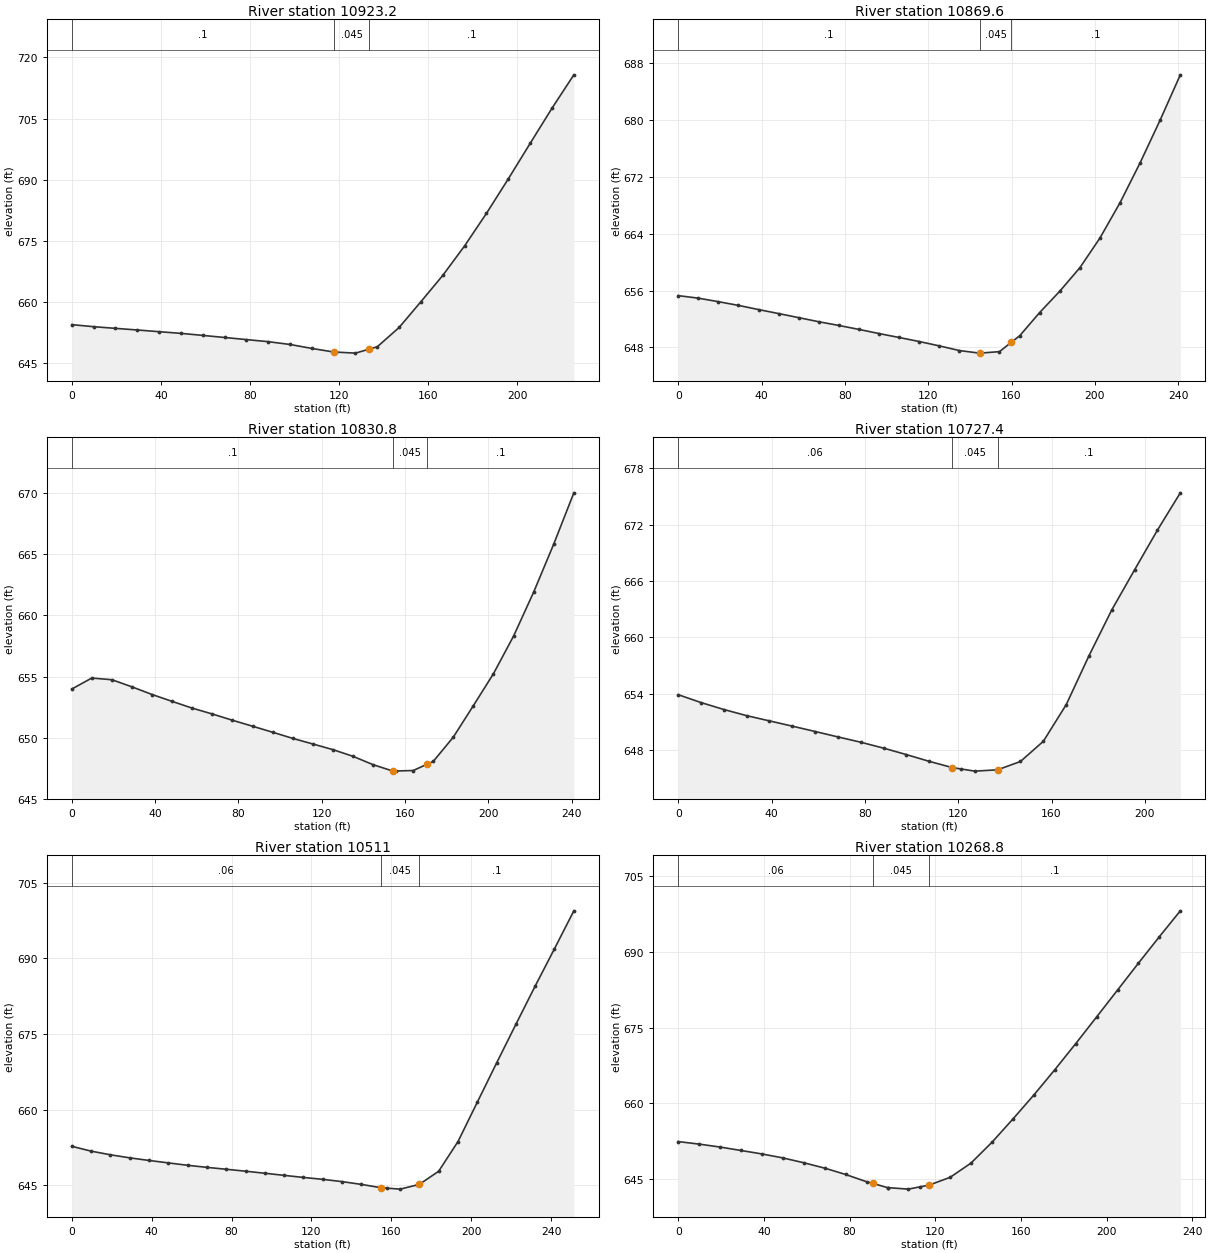
Type RM Length L Ch R = 1 ,10923.2 ,48.1,53.6,59
XS GIS Cut Line= 2
     1770767.377       558415.23     1770542.117      558411.324
#Sta/Elev= 26
       0  654.41     9.8  653.91    19.6   653.5    29.4   653.1    39.2  652.68
      49  652.27    58.8  651.77    68.6  651.26    78.4  650.74    88.2  650.23
      98  649.54   107.8  648.56   117.5   647.7   118.6  647.67   127.3  647.42
   133.6  648.42   137.1  648.98   146.9  653.72   156.7  660.06   166.5  666.51
   176.3  673.76   186.1  681.74   195.9   690.2   205.7  698.91   215.5  707.54
   225.3  715.73
#Mann= 3 , 0 , 0
       0      .1       0   117.5    .045       0   133.6      .1       0
Bank Sta=117.5,133.6
XS Rating Curve= 0 ,0
Exp/Cntr=0.3,0.1

Type RM Length L Ch R = 1 ,10869.6 ,38.7,38.8,38.9
XS GIS Cut Line= 2
     1770798.627      558399.605     1770565.554      558338.408
#Sta/Elev= 28
       0  655.28     9.6  654.93    19.3  654.43    28.9  653.91    38.6  653.32
    48.2  652.76    57.8  652.19    67.5  651.61    77.1  651.09    86.8  650.53
    96.4  649.95     106   649.4   115.7  648.83   125.3  648.22     135  647.56
   144.6   647.2   144.8   647.2   154.2  647.41   159.8   648.7   163.9  649.64
   173.5  652.91   183.1  655.89   192.8  659.21   202.4  663.37   212.1  668.36
   221.7  673.95   231.3  679.95     241  686.32
#Mann= 3 , 0 , 0
       0      .1       0   144.8    .045       0   159.8      .1       0
Bank Sta=144.8,159.8
XS Rating Curve= 0 ,0
Exp/Cntr=0.3,0.1

Type RM Length L Ch R = 1 ,10830.8 ,115.6,103.4,91.3
XS GIS Cut Line= 2
     1770815.554      558364.449     1770582.481      558303.251
#Sta/Elev= 28
       0  653.98     9.6  654.88    19.3  654.74    28.9  654.16    38.6  653.53
    48.2  652.97    57.8  652.42    67.5  651.94    77.1  651.43    86.8  650.94
    96.4  650.45     106  649.95   115.7  649.49   125.3  649.03     135  648.48
   144.6   647.8   154.2  647.27   155.5  647.28   163.9  647.32   170.5  647.83
   173.5  648.06   183.1  650.04   192.8  652.63   202.4  655.23   212.1  658.32
   221.7   661.9   231.3  665.81     241  670.02
#Mann= 3 , 0 , 0
       0      .1       0   154.2    .045       0   170.5      .1       0
Bank Sta=154.2,170.5
XS Rating Curve= 0 ,0
Exp/Cntr=0.3,0.1

Type RM Length L Ch R = 1 ,10727.4 ,215.8,216.4,216.9
XS GIS Cut Line= 2
     1770767.377      558186.064     1770560.346      558244.658
#Sta/Elev= 25
       0  653.88     9.8  653.04    19.6   652.3    29.3  651.65    39.1  651.09
    48.9  650.53    58.7  649.96    68.5  649.38    78.2  648.82      88  648.19
    97.8   647.5   107.6  646.78   117.4  646.12   121.2  645.97   127.1  645.74
   136.2  645.87   136.9  645.88   146.7  646.77   156.5  648.92   166.3  652.82
     176     658   185.8   662.9   195.6  667.18   205.4  671.41   215.2  675.38
#Mann= 3 , 0 , 0
       0     .06       0   117.4    .045       0   136.9      .1       0
Bank Sta=117.4,136.9
XS Rating Curve= 0 ,0
Exp/Cntr=0.3,0.1

Type RM Length L Ch R = 1 ,10511   ,236.4,242.2,247.8
XS GIS Cut Line= 2
     1770747.846       557971.22     1770504.356       558033.72
#Sta/Elev= 29
       0  652.72     9.7  651.76    19.3  651.04      29  650.43    38.7  649.91
    48.3  649.43      58  648.95    67.7  648.54    77.4  648.16      87  647.78
    96.7  647.37   106.4  646.95     116  646.54   125.7  646.16   135.4  645.71
     145  645.16   154.7  644.51   157.9  644.41   164.4  644.22   172.9  645.05
     174  645.16   183.7  647.76   193.4  653.67     203  661.43   212.7  669.24
   222.4  676.95     232   684.5   241.7  691.93   251.4  699.46
#Mann= 3 , 0 , 0
       0     .06       0   154.7    .045       0     174      .1       0
Bank Sta=154.7,174
XS Rating Curve= 0 ,0
Exp/Cntr=0.3,0.1

Type RM Length L Ch R = 1 ,10268.8 ,138.2,138.4,138.4
XS GIS Cut Line= 2
     1770749.148      557779.814     1770514.773      557781.116
#Sta/Elev= 28
       0  652.43     9.8  651.93    19.5  651.35    29.3  650.67    39.1  649.98
    48.8   649.2    58.6  648.24    68.4  647.17    78.1  645.92    87.9  644.48
   91.01  644.13    97.7  643.31    98.1   643.3   107.4  643.01   113.1  643.48
   117.2  643.82     127  645.36   136.7  648.18   146.5  652.31   156.2  656.88
     166  661.65   175.8  666.67   185.6  671.86   195.3  677.12   205.1  682.46
   214.8  687.76   224.6  693.02   234.4  698.16
#Mann= 3 , 0 , 0
       0     .06       0   91.01    .045       0   117.2      .1       0
Bank Sta=91.01,117.2
XS Rating Curve= 0 ,0
Exp/Cntr=0.3,0.1

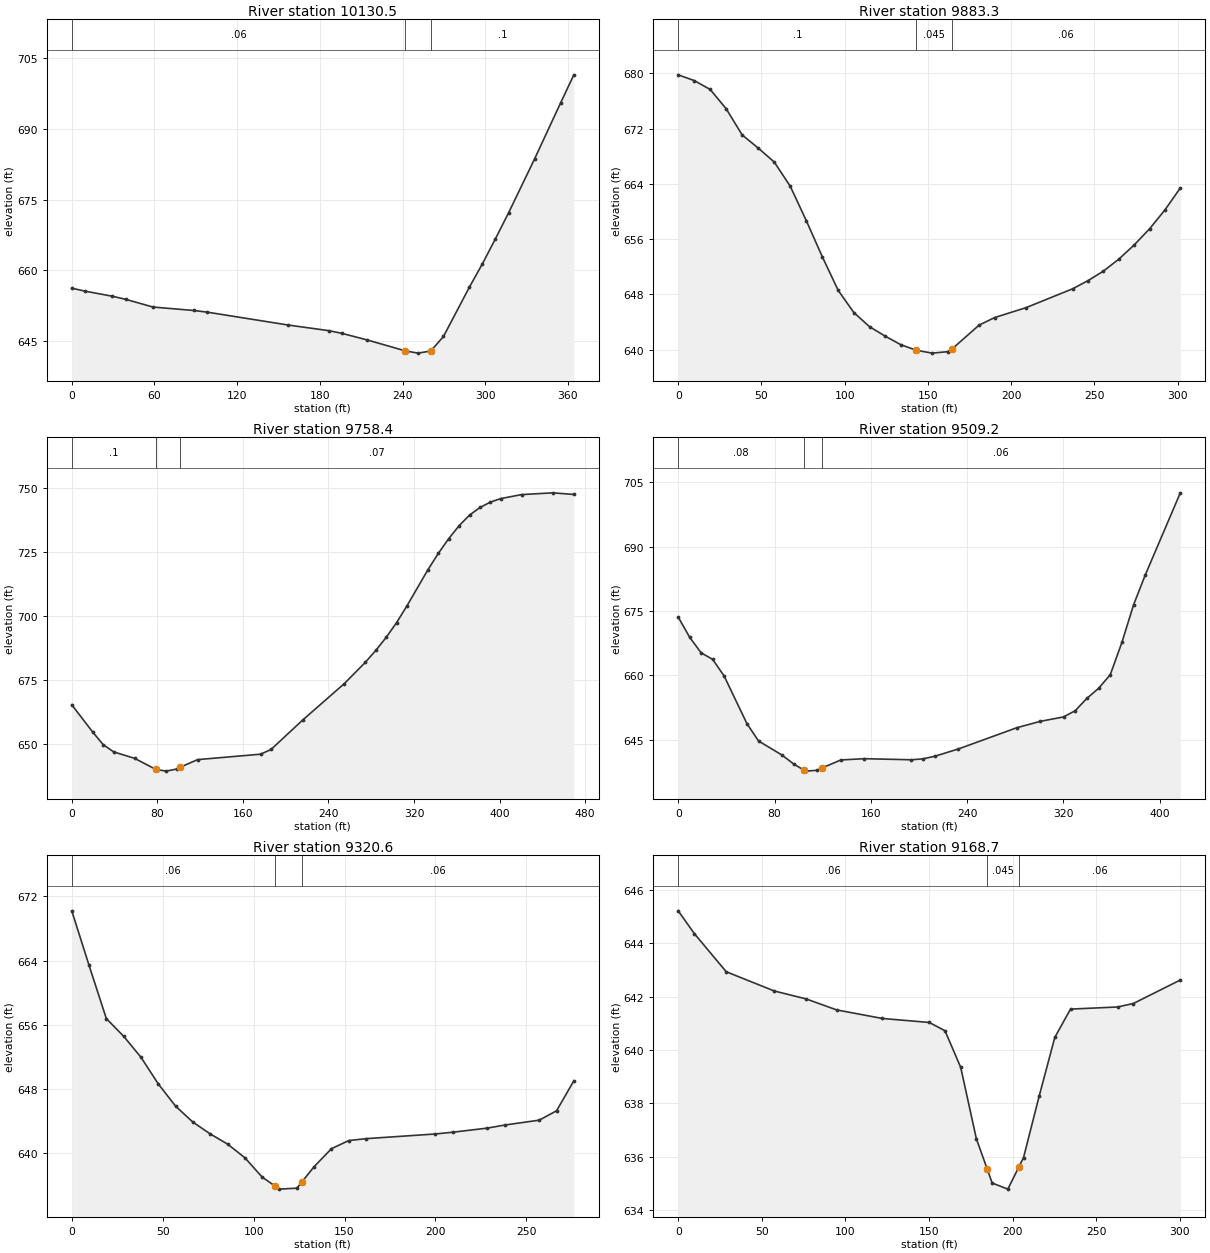
Type RM Length L Ch R = 1 ,10130.5 ,259.1,247.2,234.2
XS GIS Cut Line= 4
     1770859.319      557719.339      1770687.95      557645.699
     1770595.502      557645.699     1770516.075      557676.949
#Sta/Elev= 22
       0  656.15     9.8  655.51    29.4  654.44    39.3  653.77    58.9  652.14
    88.4  651.41    98.2  651.06   157.1  648.31   186.5  647.12   195.8  646.56
   214.3  645.15     242  642.82   251.2  642.34   260.5  642.79   269.7  645.88
   288.4  656.31   297.9   661.3   307.4  666.65   316.9  672.15   335.9  683.69
   354.8  695.62   364.3  701.52
#Mann= 3 , 0 , 0
       0     .06       0     242    .045       0   260.5      .1       0
Bank Sta=242,260.5
XS Rating Curve= 0 ,0
Exp/Cntr=0.3,0.1

Type RM Length L Ch R = 1 ,9883.3  ,121.7,124.8,128.5
XS GIS Cut Line= 4
     1770763.833      557304.409     1770697.065      557373.564
     1770579.877       557433.46     1770508.263      557451.689
#Sta/Elev= 30
       0  679.79     9.6  678.96    19.2  677.67    28.8  674.88    38.4  671.09
    48.1  669.18    57.7  667.16    67.3  663.66    76.9   658.7    86.5  653.48
    96.1  648.59   105.5  645.38   114.9  643.34   124.3  641.97   133.7  640.73
   143.1  639.92   152.5  639.51   161.9  639.72  164.61  640.14   180.7  643.56
   190.1  644.66   208.9  646.09     237  648.83   246.2  650.01   255.4  651.38
   264.7  653.12   273.9  655.17   283.2  657.52   292.4  660.25   301.6  663.41
#Mann= 3 , 0 , 0
       0      .1       0   143.1    .045       0  164.61     .06       0
Bank Sta=143.1,164.61
XS Rating Curve= 0 ,0
Exp/Cntr=0.3,0.1

Type RM Length L Ch R = 1 ,9758.4  ,226.6,249.2,272.4
XS GIS Cut Line= 3
      1770687.95      557251.168     1770462.226      557346.894
     1770241.336       557308.46
#Sta/Elev= 30
       0   665.2    19.6  654.53    29.4  649.61    39.2  646.79    58.8  644.26
    78.5  639.97    88.3  639.28    98.1   640.1   101.4  640.81   117.7  643.78
   176.5  645.89   186.3  647.74   215.8   659.2   254.9   673.5   274.4  681.75
   284.2   686.4   293.9  691.48   303.7   697.3   313.4  703.84   332.9  717.88
   342.7  724.32   352.4  730.07   362.2  735.17   371.9  739.28   381.7  742.25
   391.4  744.35   401.2  745.74   420.6  747.28   449.9  747.97   469.4  747.33
#Mann= 3 , 0 , 0
       0      .1       0    78.5    .045       0   101.4     .07       0
Bank Sta=78.5,101.4
XS Rating Curve= 0 ,0
Exp/Cntr=0.3,0.1

Type RM Length L Ch R = 1 ,9509.2  ,186.5,188.6,190.3
XS GIS Cut Line= 4
     1770707.481      557137.887     1770642.377      557123.564
     1770497.846      557023.303     1770391.075      556885.283
#Sta/Elev= 30
       0  673.55     9.5  668.86      19  665.23    28.6   663.7    38.1  659.83
    57.1  648.69    66.7  644.66    86.2  641.37      96  639.27   104.5  637.84
   105.8  637.62   115.5  637.82   119.5  638.36   135.1  640.23   154.6  640.52
   193.7  640.27   203.5  640.49   213.2   641.1   232.8   642.8   281.3  647.75
   300.7  649.23   320.1  650.27   329.8  651.72   339.5   654.6   349.2  656.94
   358.9  660.11   368.6  667.67   378.3  676.45     388  683.41   417.1  702.56
#Mann= 3 , 0 , 0
       0     .08       0   104.5    .045       0   119.5     .06       0
Bank Sta=104.5,119.5
XS Rating Curve= 0 ,0
Exp/Cntr=0.3,0.1

Type RM Length L Ch R = 1 ,9320.6  ,178.6,151.9,124.5
XS GIS Cut Line= 2
     1770772.586      557007.678      1770562.95      556827.991
#Sta/Elev= 27
       0  670.18     9.5   663.4      19  656.78    28.6  654.56    38.1  651.95
    47.6  648.64    57.1  645.88    66.6   643.9    76.2  642.42    85.7  641.16
    95.2  639.46   104.7  637.06   111.6  635.97   114.2  635.56   123.8  635.68
   126.6  636.47   133.3  638.36   142.8  640.59   152.3   641.6   161.9  641.84
   199.9  642.42   209.5  642.64   228.5  643.15     238  643.53   257.1  644.14
   266.6  645.31   276.1  649.03
#Mann= 3 , 0 , 0
       0     .06       0   111.6    .045       0   126.6     .06       0
Bank Sta=111.6,126.6
XS Rating Curve= 0 ,0
Exp/Cntr=0.3,0.1

Type RM Length L Ch R = 1 ,9168.7  ,157.3,68,61.8
XS GIS Cut Line= 4
     1770896.283      556713.408     1770823.367      556736.845
       1770781.7      556755.074      1770618.94      556827.991
#Sta/Elev= 22
       0  645.21     9.6  644.36    28.7  642.93    57.4  642.21    76.6  641.91
    94.8   641.5   122.1  641.18   150.2  641.03   159.6  640.72     169  639.35
   178.4  636.67  184.77  635.56   187.8  635.02   197.2  634.79   203.8  635.62
   206.6  635.97   215.9  638.26   225.3  640.47   234.7  641.53   262.9  641.61
   272.3  641.74   300.4  642.62
#Mann= 3 , 0 , 0
       0     .06       0  184.77    .045       0   203.8     .06       0
Bank Sta=184.77,203.8
XS Rating Curve= 0 ,0
Exp/Cntr=0.3,0.1

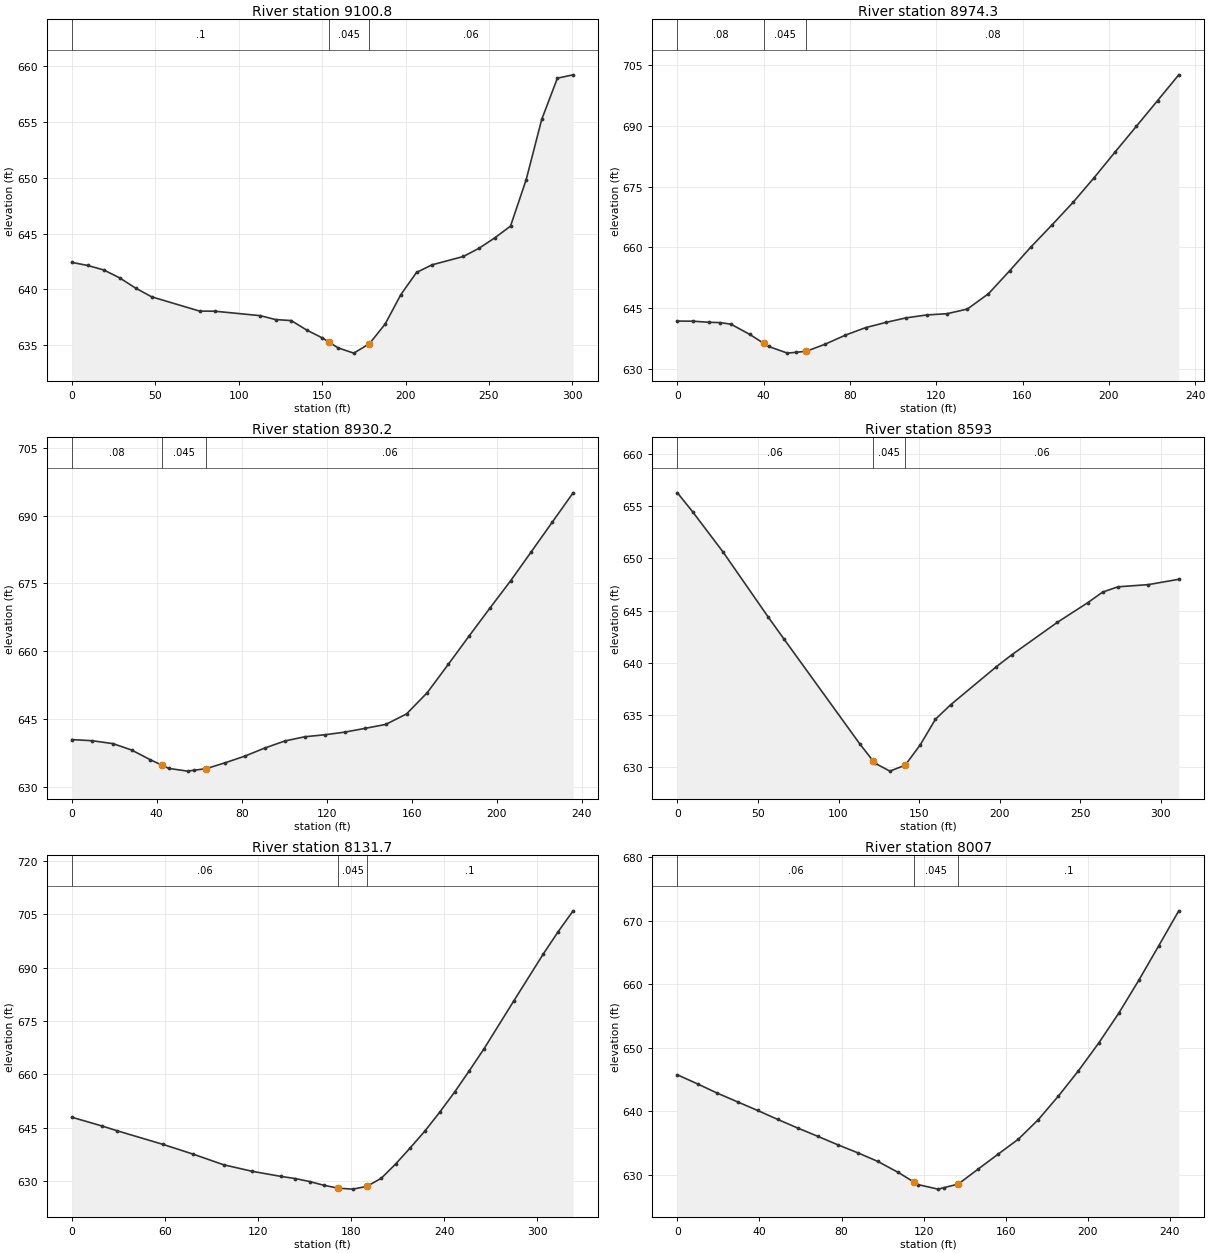
Type RM Length L Ch R = 1 ,9100.8  ,28.1,126.5,155.8
XS GIS Cut Line= 4
     1770880.658      556662.626     1770807.742      556686.064
     1770766.075      556704.293     1770603.315       556777.21
#Sta/Elev= 29
       0  642.43     9.6  642.15    19.2  641.75    28.7  641.04    38.3  640.12
    47.9  639.34    76.6  638.06    85.7  638.05     113  637.65   122.1   637.3
   131.5  637.21   140.8  636.36   150.2  635.65   154.2  635.27   159.6  634.76
     169  634.29   178.4  635.14   187.8   636.9   197.2  639.54   206.6  641.53
   215.9  642.21   234.7  642.96   244.1   643.7   253.5  644.63   262.9  645.68
   272.3  649.85   281.6  655.25     291  658.95   300.4  659.25
#Mann= 3 , 0 , 0
       0      .1       0   154.2    .045       0   178.4     .06       0
Bank Sta=154.2,178.4
XS Rating Curve= 0 ,0
Exp/Cntr=0.3,0.1

Type RM Length L Ch R = 1 ,8974.3  ,29.2,44.1,44.9
XS GIS Cut Line= 6
     1770877.331       556655.61     1770863.442       556659.95
     1770854.832      556665.523     1770818.158      556641.793
     1770760.867      556609.241     1770671.023      556570.178
#Sta/Elev= 29
       0  641.84     7.3  641.81    14.6  641.54    19.7  641.47    24.8  641.08
    33.5  638.57      40  636.36    42.3  635.58      51  633.94      55  634.15
    59.8   634.4    68.5  636.15    77.9  638.38    87.3  640.23    96.7  641.52
   106.1  642.64   115.6  643.35     125  643.66   134.4   644.8   144.2  648.58
     154  654.23   163.8  660.07   173.6  665.51   183.4   671.1   193.2   677.2
     203  683.58   212.8  689.88   222.6  696.19   232.4  702.53
#Mann= 3 , 0 , 0
       0     .08       0      40    .045       0    59.8     .08       0
Bank Sta=40,59.8
XS Rating Curve= 0 ,0
Exp/Cntr=0.3,0.1

Type RM Length L Ch R = 1 ,8930.2  ,337.1,337.2,337.2
XS GIS Cut Line= 5
     1770910.172      556645.699     1770891.943      556639.189
     1770847.672      556610.543     1770790.381      556577.991
     1770700.537      556538.928
#Sta/Elev= 28
       0  640.43     9.7  640.17    19.4  639.53    28.2  638.11    36.9  635.98
    42.5  634.75    45.7  634.04    54.5  633.44    57.5  633.63    63.3  633.99
    72.1  635.27    81.5  636.76    90.9  638.56   100.3  640.11   109.7  641.05
   119.2  641.49   128.6  642.08     138   642.9   147.8  643.78   157.6   646.1
   167.4  650.84   177.2  657.05     187  663.32   196.8   669.5   206.6  675.58
   216.4  682.06   226.2  688.56     236  695.05
#Mann= 3 , 0 , 0
       0     .08       0    42.5    .045       0    63.3     .06       0
Bank Sta=42.5,63.3
XS Rating Curve= 0 ,0
Exp/Cntr=0.3,0.1

Type RM Length L Ch R = 1 ,8593    ,453.5,461.3,468.7
XS GIS Cut Line= 3
     1771127.331      556397.652     1771048.121      556346.654
     1770866.914      556227.296
#Sta/Elev= 21
       0  656.26     9.4  654.46    28.3  650.61    56.5  644.35      66  642.31
   113.1  632.27   121.4  630.63   122.5  630.41   131.9  629.64   141.4  630.21
   150.8  632.17   160.2  634.61   169.7     636     198  639.63   207.4  640.75
   235.7  643.86   254.6  645.74     264  646.77   273.5  647.27   292.3  647.48
   311.2  647.99
#Mann= 3 , 0 , 0
       0     .06       0   121.4    .045       0   141.4     .06       0
Bank Sta=121.4,141.4
XS Rating Curve= 0 ,0
Exp/Cntr=0.3,0.1

Type RM Length L Ch R = 1 ,8131.7  ,127.8,124.7,121.6
XS GIS Cut Line= 4
     1771474.553      556096.003     1771379.067      556074.302
     1771306.367      555978.816     1771223.902      555913.711
#Sta/Elev= 26
       0  647.94    19.6  645.45    29.4   644.1    58.8  640.29    78.3  637.53
    97.9  634.55   116.4   632.7   134.8  631.28   144.1  630.67   153.3  629.83
   162.5  628.78   171.8  627.96     181   627.7   190.2  628.48   199.5  630.79
   208.7  634.79   217.9  639.22   227.5  644.03     237   649.3   246.6  654.97
   256.1  660.98   265.7  667.25   284.8  680.66   303.9  693.93   313.4  700.14
     323     706
#Mann= 3 , 0 , 0
       0     .06       0   171.8    .045       0   190.2      .1       0
Bank Sta=171.8,190.2
XS Rating Curve= 0 ,0
Exp/Cntr=0.3,0.1

Type RM Length L Ch R = 1 ,8007    ,140.7,140.6,140.5
XS GIS Cut Line= 2
      1771520.56      556028.005     1771347.817      555855.262
#Sta/Elev= 28
       0  645.72     9.8  644.29    19.5  642.82    29.3  641.46    39.1   640.1
    48.9  638.69    58.6  637.34    68.4  636.03    78.2  634.69      88  633.42
    97.7  632.07   107.5  630.36   115.1  628.86   117.3  628.42     127  627.71
   130.1  627.96   136.8   628.5   146.6  630.88   156.4  633.25   166.1  635.57
   175.9  638.67   185.7  642.39   195.4  646.35   205.2  650.68     215  655.39
   224.8   660.6   234.5  666.02   244.3  671.55
#Mann= 3 , 0 , 0
       0     .06       0   115.1    .045       0   136.8      .1       0
Bank Sta=115.1,136.8
XS Rating Curve= 0 ,0
Exp/Cntr=0.3,0.1

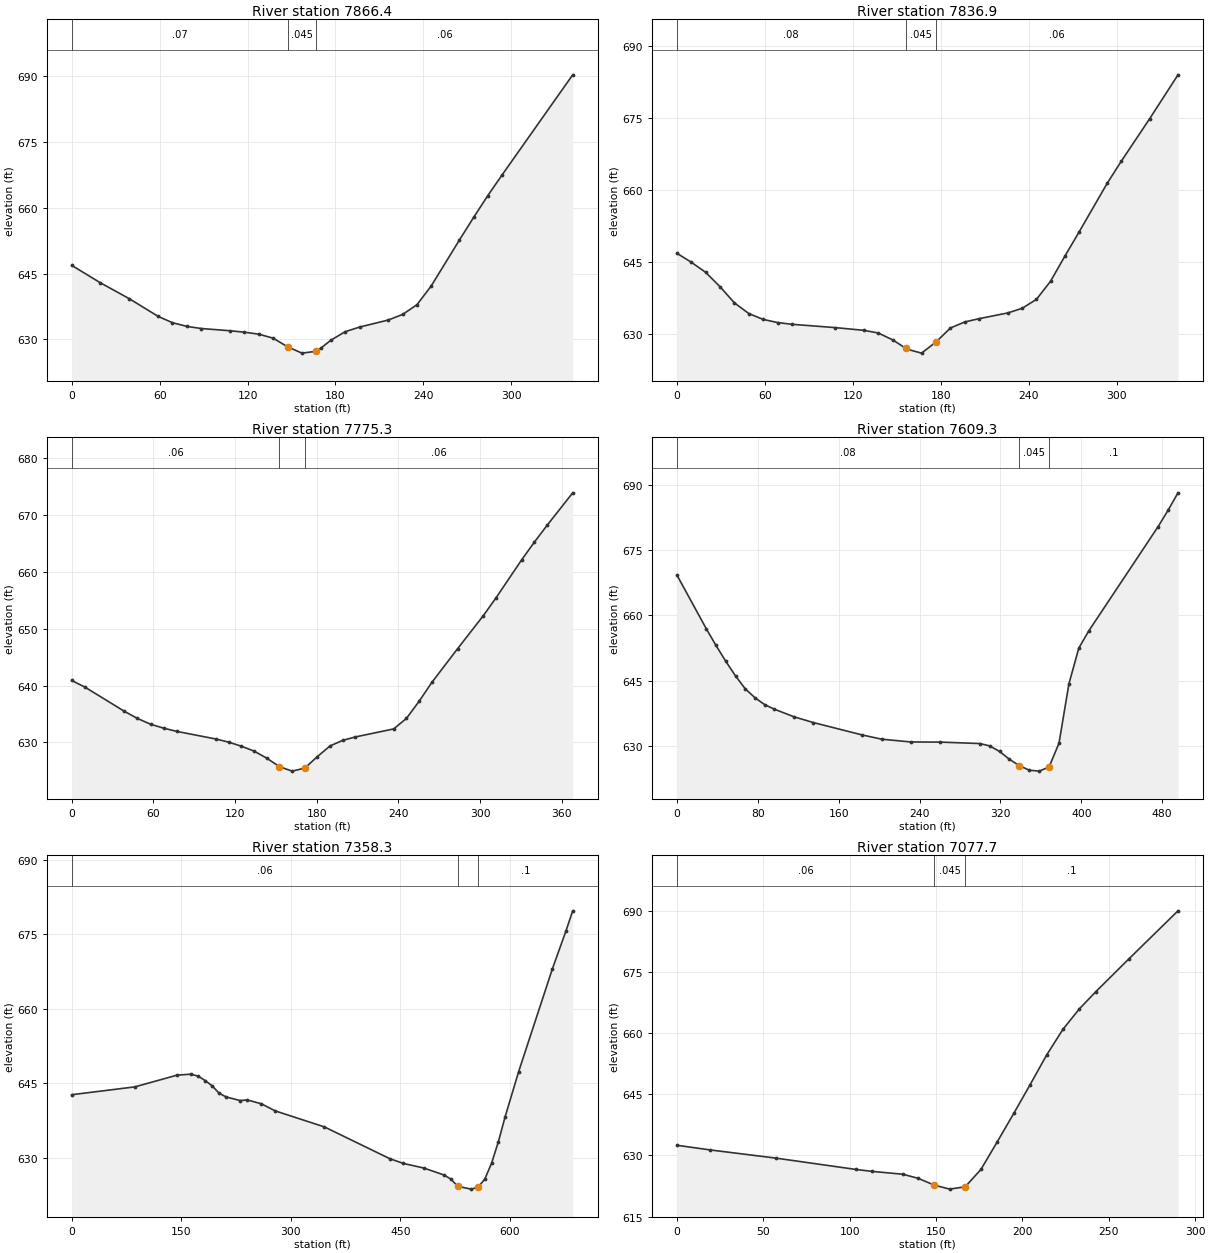
Type RM Length L Ch R = 1 ,7866.4  ,29.5,29.5,29.5
XS GIS Cut Line= 4
     1771595.213      555982.939     1771561.576      555870.092
     1771484.536      555794.137     1771381.454      555740.968
#Sta/Elev= 27
       0  646.89    19.6   642.9    39.2   639.3    58.9  635.26    68.7  633.81
    78.5  632.97    88.3  632.48   107.9  631.97   117.8  631.64   127.6  631.19
   137.4  630.28   147.3  628.31   157.1  626.86   166.9  627.28  169.88  627.96
   176.8   629.8   186.6  631.75   196.4   632.8   216.1  634.42   225.9   635.7
   235.6  637.91   245.3  642.17   264.6  652.68   274.3  657.84   283.9  662.78
   293.6  667.48   341.9  690.37
#Mann= 3 , 0 , 0
       0     .07       0   147.3    .045       0   166.9     .06       0
Bank Sta=147.3,166.9
XS Rating Curve= 0 ,0
Exp/Cntr=0.3,0.1

Type RM Length L Ch R = 1 ,7836.9  ,62.9,61.6,60.2
XS GIS Cut Line= 4
     1771617.782      555963.842     1771584.145      555850.994
     1771507.105       555775.04     1771404.024      555721.871
#Sta/Elev= 30
       0  646.76     9.8   644.9    19.6  642.79    29.4  639.79    39.2  636.43
    49.1  634.19    58.9  632.98    68.7  632.33    78.5  631.97   107.9  631.28
   127.6  630.71   137.4  630.15   147.3   628.7     156  626.99   157.1  626.77
   166.9  625.96   176.8  628.29   186.6   631.2   196.4  632.46   206.3  633.15
   225.9  634.35   235.6  635.31   245.3  637.17   254.9  640.93   264.6  646.12
   274.3  651.16   293.6  661.37   303.3  666.01   322.6  674.84   341.9  683.97
#Mann= 3 , 0 , 0
       0     .08       0     156    .045       0   176.8     .06       0
Bank Sta=156,176.8
XS Rating Curve= 0 ,0
Exp/Cntr=0.3,0.1

Type RM Length L Ch R = 1 ,7775.3  ,163.7,166.1,167.4
XS GIS Cut Line= 4
     1771723.685      555854.394     1771636.879       555811.86
     1771538.789      555725.922      1771489.31      555593.978
#Sta/Elev= 30
       0   640.9     9.7  639.73    38.7  635.47    48.3  634.21      58  633.19
    67.7  632.49    77.3  631.93     106  630.59   115.3  630.04   124.6  629.33
   133.9  628.47   143.2  627.23   152.6  625.72   161.9  624.94   171.2  625.47
   180.5  627.51   189.8  629.38   199.1  630.36   208.4  630.96   236.5  632.37
   245.9  634.23   255.3  637.28   264.6  640.58   283.4  646.48   302.2  652.26
   311.6  655.42   330.4   662.1   339.8  665.24   349.2  668.22     368  673.93
#Mann= 3 , 0 , 0
       0     .06       0   152.6    .045       0   171.2     .06       0
Bank Sta=152.6,171.2
XS Rating Curve= 0 ,0
Exp/Cntr=0.3,0.1

Type RM Length L Ch R = 1 ,7609.3  ,258.3,251,244.3
XS GIS Cut Line= 3
     1771778.373      555920.222     1771667.695      555673.911
      1771510.36      555512.236
#Sta/Elev= 30
       0  669.19    28.9  656.93    38.6  653.06    48.2  649.46    57.9  646.07
    67.5  643.12    77.2  641.06    86.8  639.48    96.4  638.44   115.7   636.7
     135  635.37   183.2  632.53   202.5  631.56   231.5  630.92   260.4  630.89
   299.5  630.56   309.3  630.03   319.1  628.75   328.9  626.94   338.7  625.48
   348.5  624.44   358.3  624.23   368.1  625.19   377.9  630.65   387.7  644.26
   397.5  652.47   407.4  656.43     476  680.36   485.8   684.1   495.6  688.09
#Mann= 3 , 0 , 0
       0     .08       0   338.7    .045       0   368.1      .1       0
Bank Sta=338.7,368.1
XS Rating Curve= 0 ,0
Exp/Cntr=0.3,0.1

Type RM Length L Ch R = 1 ,7358.3  ,283.2,280.6,277.6
XS GIS Cut Line= 5
     1772112.574      555839.927     1771967.415       555525.71
     1771883.624       555493.79     1771761.011        555427.6
     1771668.781      555365.751
#Sta/Elev= 30
       0  642.66    86.5  644.24   144.2   646.6   163.4   646.8   173.1   646.4
   182.7  645.52   192.3  644.46   201.9  642.96   211.5  642.21   230.8  641.48
   240.4  641.61   259.6  640.84   278.8   639.4   346.1  636.18   435.8  629.77
   454.4  628.82   482.2   627.9   510.1  626.49   519.4  625.66   528.7  624.21
   547.3  623.65   556.6  624.06   565.8  625.67   575.1  628.88   584.4   633.2
   593.6   638.2   612.1  647.29   658.4  668.02   676.9  675.62   686.2  679.69
#Mann= 3 , 0 , 0
       0     .06       0   528.7    .045       0   556.6      .1       0
Bank Sta=528.7,556.6
XS Rating Curve= 0 ,0
Exp/Cntr=0.3,0.1

Type RM Length L Ch R = 1 ,7077.7  ,172.8,159.1,145.4
XS GIS Cut Line= 4
     1772038.789      555229.033     1771963.919      555212.757
     1771871.689      555175.864     1771757.756      555169.354
#Sta/Elev= 20
       0   632.5    19.2  631.36    57.5  629.34   103.7  626.57   112.7  626.11
   130.8   625.4   139.8  624.38   148.9  622.74   157.9  621.75   166.9  622.33
     176  626.58   185.5  633.39     195  640.31   204.5  647.38     214   654.6
   223.5  660.94     233  665.95   242.5  670.15   261.5  678.13   290.1  689.98
#Mann= 3 , 0 , 0
       0     .06       0   148.9    .045       0   166.9      .1       0
Bank Sta=148.9,166.9
XS Rating Curve= 0 ,0
Exp/Cntr=0.3,0.1

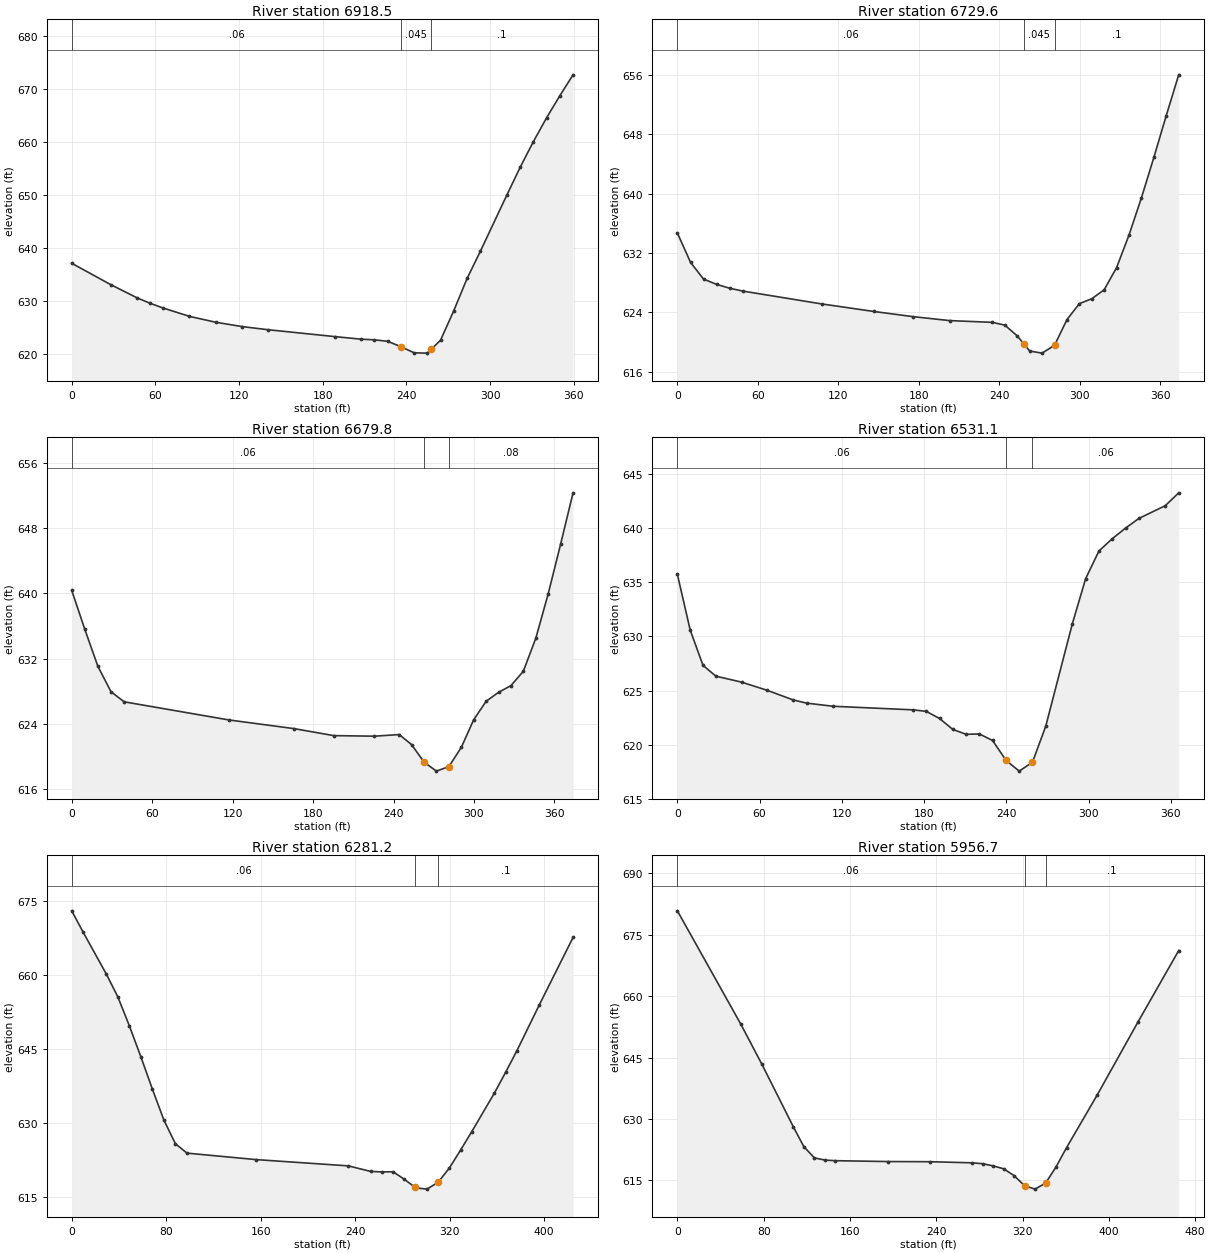
Type RM Length L Ch R = 1 ,6918.5  ,188.1,188.9,189.8
XS GIS Cut Line= 3
     1772136.445      554996.828     1772033.364      554993.572
     1771783.798      555052.166
#Sta/Elev= 27
       0  637.19    28.1  633.14    46.9  630.66    56.2  629.64    65.6  628.74
    84.4  627.17   103.1  626.07   122.1  625.24   141.1  624.64   188.6  623.35
   207.6  622.86   217.1  622.74   226.6  622.46   236.1  621.44   245.6  620.28
     255  620.23   257.9  620.98   264.5  622.68     274  628.25   283.5  634.32
     293  639.44     312  650.05   321.5  655.27     331  660.13   340.5  664.64
     350  668.81   359.5  672.76
#Mann= 3 , 0 , 0
       0     .06       0   236.1    .045       0   257.9      .1       0
Bank Sta=236.1,257.9
XS Rating Curve= 0 ,0
Exp/Cntr=0.3,0.1

Type RM Length L Ch R = 1 ,6729.6  ,49.8,49.8,49.8
XS GIS Cut Line= 4
     1772106.064       554877.47     1771915.091      554836.237
     1771884.709      554836.237      1771739.31      554864.449
#Sta/Elev= 27
       0   634.7     9.8  630.74    19.5  628.48    29.3  627.76    39.1  627.24
    48.8  626.86   107.5  625.13   146.5  624.11   175.8  623.41     203  622.88
     235  622.64   244.3  622.26   253.5  620.81   258.4  619.74   262.8  618.77
     272  618.49   281.3  619.55   290.6  623.02   299.8  625.16   309.1  625.83
   318.3  627.03   327.6  630.03   336.8   634.4   346.1  639.43   355.4   644.9
   364.6  650.52   373.9  656.03
#Mann= 3 , 0 , 0
       0     .06       0   258.4    .045       0   281.3      .1       0
Bank Sta=258.4,281.3
XS Rating Curve= 0 ,0
Exp/Cntr=0.3,0.1

Type RM Length L Ch R = 1 ,6679.8  ,138.3,148.7,158.7
XS GIS Cut Line= 4
     1772101.723      554827.557     1771910.751      554786.324
     1771880.369      554786.324      1771734.97      554814.536
#Sta/Elev= 24
       0  640.36     9.8  635.57    19.5  631.06    29.3  627.94    39.1  626.71
   117.2  624.49   166.1  623.42   195.4  622.57   225.8   622.5   244.3   622.7
   253.5  621.46   262.8  619.32     272  618.22   281.3  618.78   290.6  621.14
   299.8  624.52   309.1  626.78   318.3  627.87   327.6   628.7   336.8  630.45
   346.1  634.49   355.4  639.96   364.6  646.01   373.9  652.31
#Mann= 3 , 0 , 0
       0     .06       0   262.8    .045       0   281.3     .08       0
Bank Sta=262.8,281.3
XS Rating Curve= 0 ,0
Exp/Cntr=0.3,0.1

Type RM Length L Ch R = 1 ,6531.1  ,242.8,249.8,256.6
XS GIS Cut Line= 3
     1772086.532      554696.263     1772011.662      554693.008
     1771730.629      554618.138
#Sta/Elev= 28
       0  635.73     9.4  630.57    18.7  627.33    28.1  626.33    46.8  625.78
    65.6  625.02    84.6  624.13    94.3  623.84   113.7  623.55   171.9  623.22
   181.6  623.08   191.3  622.42     201  621.41   210.7  620.96   220.4  620.99
     230  620.39   239.8  618.56   249.4  617.56   259.1  618.38   268.8  621.71
   288.2  631.17   297.9  635.33   307.6  637.89   317.3  639.02     327     640
   336.7  640.89   356.1  642.08   365.8  643.26
#Mann= 3 , 0 , 0
       0     .06       0   239.8    .045       0   259.1     .06       0
Bank Sta=239.8,259.1
XS Rating Curve= 0 ,0
Exp/Cntr=0.3,0.1

Type RM Length L Ch R = 1 ,6281.2  ,328.9,324.5,320.1
XS GIS Cut Line= 4
     1772206.975      554587.757     1772009.492      554461.888
     1771929.197       554410.89     1771859.753      554345.786
#Sta/Elev= 28
       0  673.03     9.8  668.65    29.3  660.22      39  655.63    48.8  649.74
    58.6  643.43    68.3  636.92    78.1  630.62    87.8  625.86    97.6  623.96
   156.1  622.65   234.2  621.38   253.2  620.25   262.7  620.16   272.2  620.18
   281.7  618.65   290.7  617.04   291.3  616.93   300.8  616.67   310.3  618.06
   319.8  620.96   329.3  624.59   338.8  628.34   357.9  636.12   367.4  640.33
   376.9  644.68   395.9  653.97   424.5  667.64
#Mann= 3 , 0 , 0
       0     .06       0   290.7    .045       0   310.3      .1       0
Bank Sta=290.7,310.3
XS Rating Curve= 0 ,0
Exp/Cntr=0.3,0.1

Type RM Length L Ch R = 1 ,5956.7  ,301.5,293,284.5
XS GIS Cut Line= 4
     1772422.904      554294.788     1772305.026      554225.418
     1772096.298      554143.963     1772005.152       554094.05
#Sta/Elev= 24
       0   680.8    58.6  653.25    78.2  643.45   107.5  628.11   117.2  623.27
     127  620.52   136.8  619.98   146.5  619.83   195.2  619.62   234.2  619.58
   273.2  619.31   282.9   619.1   292.6  618.57   302.4  617.86   312.1  616.21
   321.9  613.73   322.4  613.69   331.6  612.89   341.4  614.36   351.1  618.31
   360.8     623   389.2  635.84     427  653.65   464.8  671.11
#Mann= 3 , 0 , 0
       0     .06       0   322.4    .045       0   341.4      .1       0
Bank Sta=322.4,341.4
XS Rating Curve= 0 ,0
Exp/Cntr=0.3,0.1

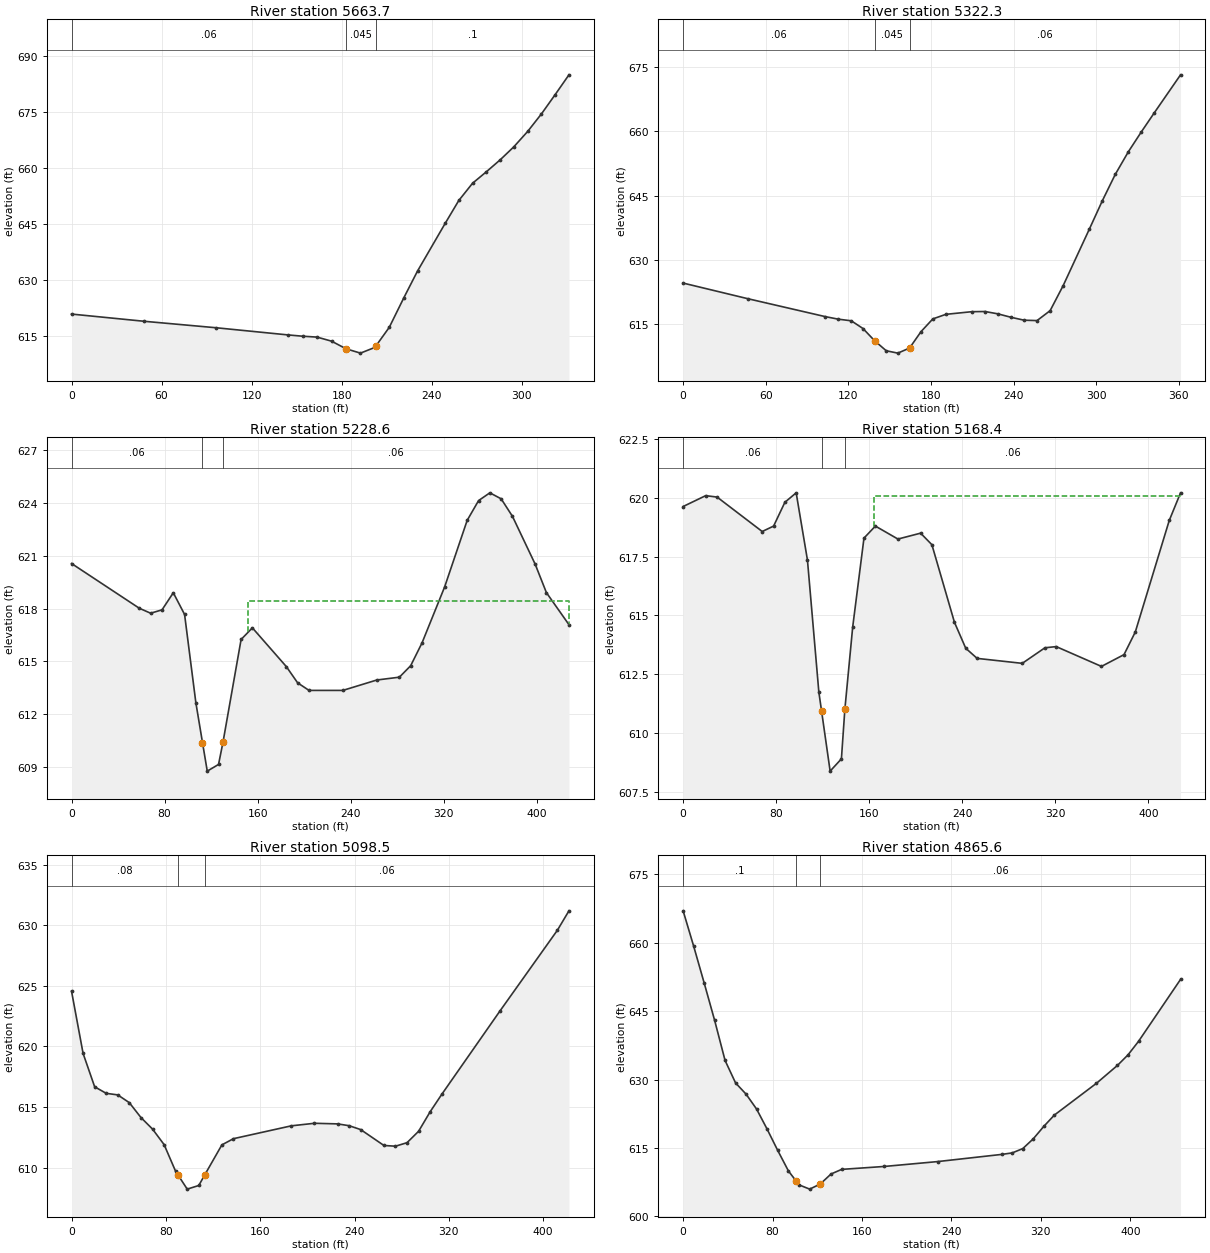
Type RM Length L Ch R = 1 ,5663.7  ,337.6,341.4,345.2
XS GIS Cut Line= 3
      1772362.14        553865.1     1772140.786      553866.185
     1772032.279      553884.632
#Sta/Elev= 24
       0  620.83    48.1  618.91    96.2  617.17   144.4  615.24     154   614.9
   163.6  614.66   173.2  613.58   182.9  611.53   192.5  610.37   202.1   611.9
   202.6  612.18   211.7  617.29   221.4   625.2   230.5  632.35   248.9   645.1
     258  651.25   267.2  655.88   276.4  658.95   285.6  662.15   294.7  665.64
   303.9  669.75   313.1  674.46   322.2   679.6   331.4  684.91
#Mann= 3 , 0 , 0
       0     .06       0   182.9    .045       0   202.6      .1       0
Bank Sta=182.9,202.6
XS Rating Curve= 0 ,0
Exp/Cntr=0.3,0.1

Type RM Length L Ch R = 1 ,5322.3  ,89.4,93.7,97.9
XS GIS Cut Line= 4
     1772346.949      553582.982     1772236.055      553531.839
     1772177.678      553522.218     1772005.152      553573.217
#Sta/Elev= 28
       0  624.58      47  620.93   103.3  616.74   112.7  616.15   122.1  615.77
   130.6  613.97     139  611.13   147.5  608.77   155.9  608.22   164.4   609.4
   172.8  613.26   181.3  616.21   190.8  617.28   209.7   617.9   219.2  617.94
   228.6  617.39   238.1  616.59   247.6  615.91     257  615.82   266.5  618.14
     276  624.01   294.9  637.13   304.4   643.8   313.8  649.97   323.3  655.25
   332.8  659.93   342.2  664.38   361.2  673.22
#Mann= 3 , 0 , 0
       0     .06       0     139    .045       0   164.4     .06       0
Bank Sta=139,164.4
XS Rating Curve= 0 ,0
Exp/Cntr=0.3,0.1

Type RM Length L Ch R = 1 ,5228.6  ,60.2,60.1,60.2
XS GIS Cut Line= 2
     1772338.268      553476.645     1771936.793      553329.076
#Sta/Elev= 30
       0  620.56    58.3  618.02      68  617.74    77.8  617.93    87.5   618.9
    97.2  617.67   106.9  612.66   112.6   610.4   116.7  608.78   126.4  609.16
   130.2  610.41   145.8  616.25   155.5  616.91   184.7  614.71   194.4  613.79
   204.2  613.36   233.3  613.36   262.5  613.95   281.9  614.11   291.6  614.76
   301.4  616.06   320.8  619.23   340.2  623.01     350  624.13   359.7  624.57
   369.4  624.23   379.1  623.24   398.6  620.53   408.3  618.91   427.7  617.09
#Mann= 3 , 0 , 0
       0     .06       0   112.6    .045       0   130.2     .06       0
#XS Ineff= 2 , 0
                           151.9          618.45
Permanent Ineff=
       F       F
Bank Sta=112.6,130.2
XS Rating Curve= 0 ,0
Exp/Cntr=0.3,0.1

Type RM Length L Ch R = 1 ,5168.4  ,67.9,69.9,71.8
XS GIS Cut Line= 2
     1772371.906      553425.647      1771970.43      553278.078
#Sta/Elev= 30
       0  619.62    19.4  620.08    29.2  620.02      68  618.56    77.8  618.79
    87.5   619.8    97.2   620.2   106.9  617.35   116.7  611.75     119  610.96
   126.4   608.4   136.1  608.92  139.06  611.02   145.8  614.51   155.5  618.28
   165.3  618.79   184.7  618.24   204.2  618.49   213.9     618   233.3  614.71
     243  613.61   252.8  613.18   291.6  612.97   311.1  613.63   320.8  613.68
   359.7  612.84   379.1  613.34   388.8   614.3     418  619.03   427.7   620.2
#Mann= 3 , 0 , 0
       0     .06       0     119    .045       0  139.06     .06       0
#XS Ineff= 2 , 0
                           164.3          620.07
Permanent Ineff=
       F       F
Bank Sta=119,139.06
XS Rating Curve= 0 ,0
Exp/Cntr=0.3,0.1

Type RM Length L Ch R = 1 ,5098.5  ,229.5,232.9,236.1
XS GIS Cut Line= 2
     1772376.246      553362.713     1771994.301      553183.677
#Sta/Elev= 30
       0  624.55     9.8  619.42    19.6  616.67    29.4  616.13    39.2     616
      49  615.36    58.9  614.13    68.7  613.18    78.5   611.9    88.3  609.69
    90.2  609.41    98.1  608.23   107.9  608.53  112.93   609.4   127.5  611.88
   137.3  612.39   186.4  613.45     206  613.66   225.6  613.61   235.4  613.46
   245.2  613.14   264.9  611.83   274.7  611.77   284.5  612.06   294.3     613
   304.1  614.61   313.9  616.04     363  622.88     412  629.58   421.8  631.18
#Mann= 3 , 0 , 0
       0     .08       0    90.2    .045       0  112.93     .06       0
Bank Sta=90.2,112.93
XS Rating Curve= 0 ,0
Exp/Cntr=0.3,0.1

Type RM Length L Ch R = 1 ,4865.6  ,569.8,572.5,573.7
XS GIS Cut Line= 4
     1772471.732      553173.911     1772412.053      553128.338
     1772221.081       553002.47     1772088.702      552953.642
#Sta/Elev= 30
       0  667.02     9.4  659.29    18.8  651.22    28.2  642.98    37.5  634.22
    46.9  629.28    56.3  626.82    65.7  623.55    75.1  619.16    84.6  614.48
    94.2  609.97   100.9  607.82   103.7  606.92   113.2  605.99   122.7  607.12
   132.3  609.31   141.8  610.32   179.9  610.96   227.6  612.03   284.8   613.6
   294.3  613.93   303.8  614.88   313.2  617.03   322.6  619.75     332  622.22
   369.7   629.2   388.5  633.13   397.9  635.43   407.3  638.39   444.9  651.98
#Mann= 3 , 0 , 0
       0      .1       0   100.9    .045       0   122.7     .06       0
Bank Sta=100.9,122.7
XS Rating Curve= 0 ,0
Exp/Cntr=0.3,0.1