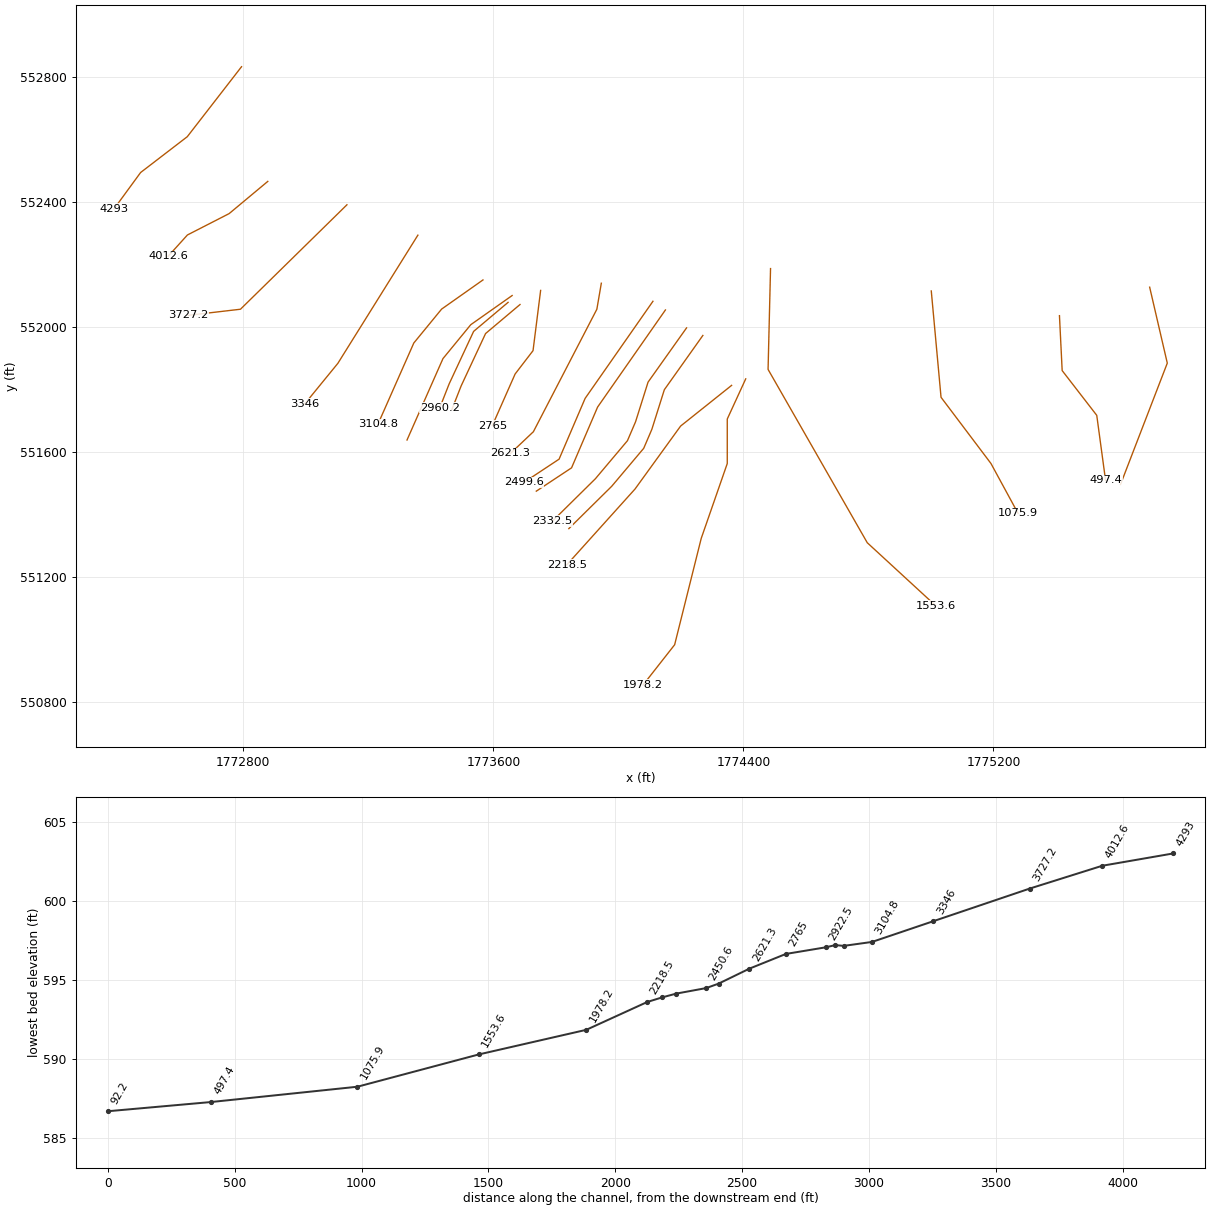
HEC-RAS study DERRICKCK.prj: DERRICKCK

--- DERRICKCK.g01 (geometry) --- (continued)

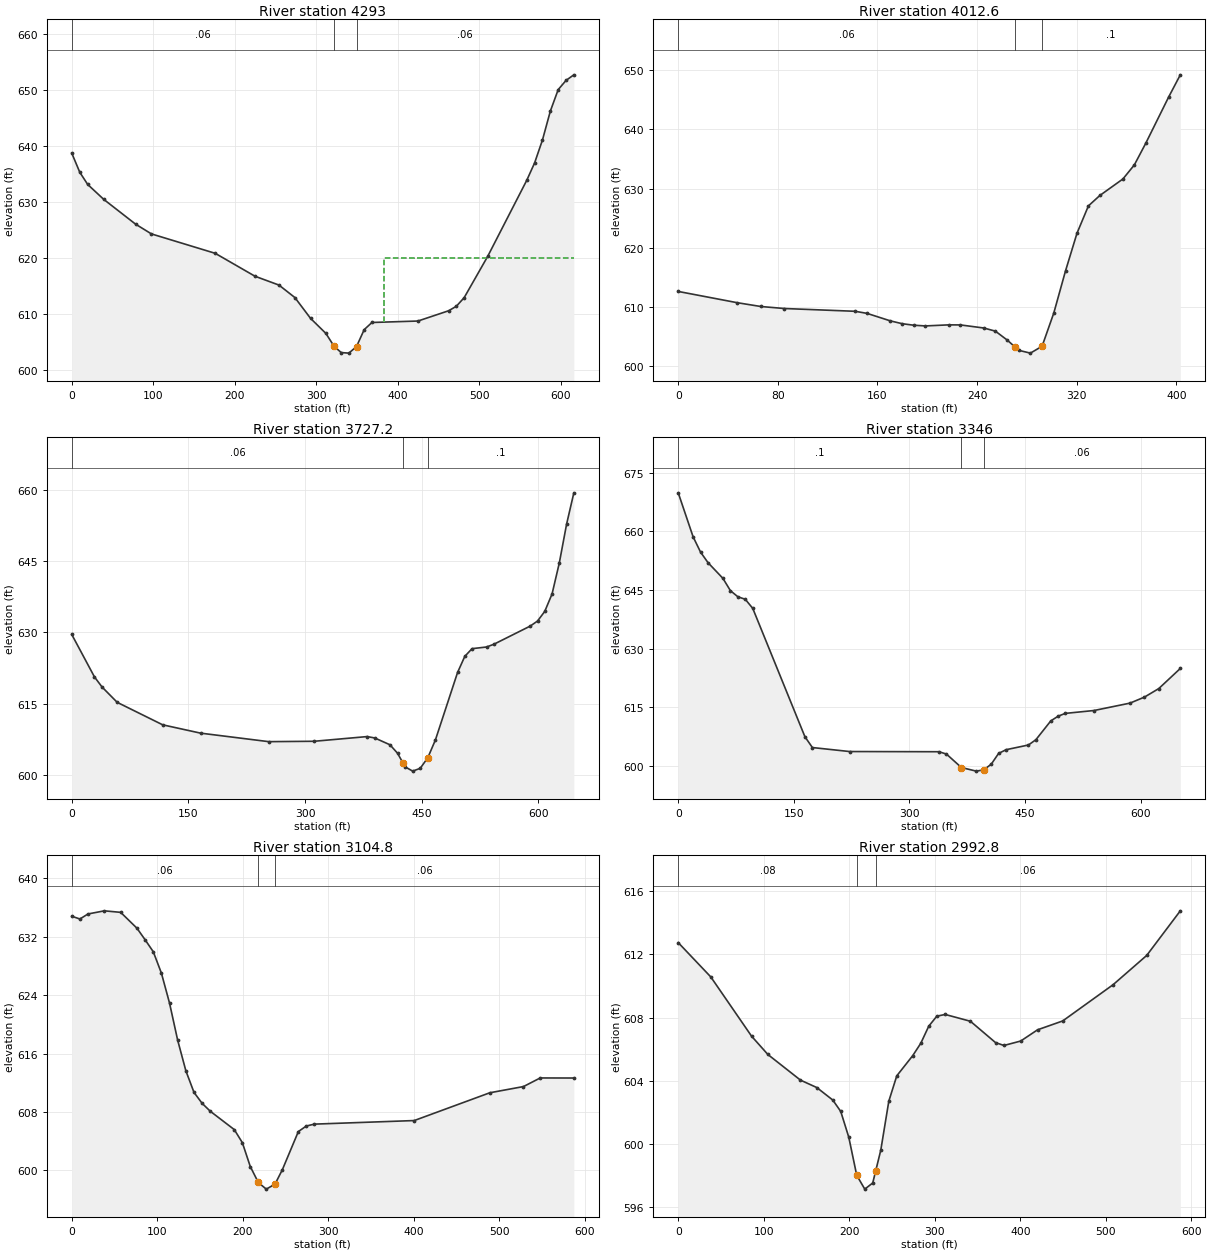
Type RM Length L Ch R = 1 ,4293    ,285.3,280.4,276.3
XS GIS Cut Line= 4
     1772794.215      552832.331     1772620.603      552608.373
     1772471.298       552493.79     1772386.228       552377.47
#Sta/Elev= 30
       0  638.77     9.8  635.36    19.5  633.18    39.1  630.52    78.2  626.08
    97.7  624.33   175.9  620.86   224.7  616.76   254.1  615.18   273.6  612.95
   292.8  609.23   311.6  606.54   321.7  604.23   330.4  603.11   339.8  603.01
   349.2  604.19   358.6  607.21   368.1  608.49   424.5  608.75   462.2  610.59
   471.6  611.39   481.2  612.93     510   620.3     558  633.93   567.6  637.03
   577.2  641.12   586.9   646.3   596.5  650.13   606.1  651.78   615.7  652.78
#Mann= 3 , 0 , 0
       0     .06       0   321.7    .045       0   349.2     .06       0
#XS Ineff= 2 , 0
       0                     383       0     620
Permanent Ineff=
       F       F
Bank Sta=321.7,349.2
XS Rating Curve= 0 ,0
Exp/Cntr=0.3,0.1

Type RM Length L Ch R = 1 ,4012.6  ,278.1,285.4,291.7
XS GIS Cut Line= 4
     1772878.199      552465.343     1772754.501      552362.261
     1772621.037      552293.902     1772559.189      552225.542
#Sta/Elev= 29
       0  612.64    47.4  610.74    66.3   610.1    85.2  609.76   142.1  609.29
   151.6  608.94   170.4  607.67   179.8   607.2   189.1  606.94   198.5  606.82
   217.2     607   226.6  606.99   245.4  606.47   254.7  605.94   264.1  604.45
   270.7  603.22   273.5   602.7   282.8  602.23   292.2  603.39   301.6     609
     311   616.1   320.2  622.45   329.4  627.08   338.6  628.84   357.1  631.62
   366.3     634   375.5  637.67   393.9  645.48   403.2   649.2
#Mann= 3 , 0 , 0
       0     .06       0   270.7    .045       0   292.2      .1       0
Bank Sta=270.7,292.2
XS Rating Curve= 0 ,0
Exp/Cntr=0.3,0.1

Type RM Length L Ch R = 1 ,3727.2  ,380.9,381.2,382.8
XS GIS Cut Line= 3
     1773131.454      552390.491     1772790.742       552056.29
     1772623.642      552036.758
#Sta/Elev= 30
       0  629.53    29.2   620.6      39  618.47    58.4  615.26   116.9  610.53
   165.6  608.78   253.2  606.99   311.7  607.07   379.9  608.06   389.6  607.76
   409.1  606.33   418.8  604.56   426.1  602.42   428.6  601.69   438.3  600.79
     448  601.38   457.8  603.63   467.5  607.34     496  621.54   505.3  624.93
   514.6  626.55   533.3   626.9   542.7  627.48   589.4   631.3   598.8  632.36
   608.1  634.39   617.5  638.06   626.8  644.57   636.2  652.76   645.5  659.33
#Mann= 3 , 0 , 0
       0     .06       0   426.1    .045       0   457.8      .1       0
Bank Sta=426.1,457.8
XS Rating Curve= 0 ,0
Exp/Cntr=0.3,0.1

Type RM Length L Ch R = 1 ,3346    ,240.8,241.2,238
XS GIS Cut Line= 3
     1773358.451      552293.269     1773102.374      551883.112
     1772996.037      551752.904
#Sta/Elev= 30
       0  669.88    19.3  658.63      29  654.71    38.7  652.01      58  648.01
    67.7  644.87    77.4   643.3      87  642.66    96.7  640.34   164.4  607.52
   174.1  604.75   222.4  603.73   338.5  603.68   348.1  603.08   367.5  599.64
   386.8  598.72   396.5  599.05   406.2  600.49   415.8  603.25   425.5   604.2
   454.5   605.4   464.2  606.76   483.5  611.56   492.9  612.75   502.2  613.48
   539.6  614.22   586.3  616.11     605  617.64   623.6  619.82   651.6  624.97
#Mann= 3 , 0 , 0
       0      .1       0   367.5    .045       0   396.5     .06       0
Bank Sta=367.5,396.5
XS Rating Curve= 0 ,0
Exp/Cntr=0.3,0.1

Type RM Length L Ch R = 1 ,3104.8  ,110.9,112,115.5
XS GIS Cut Line= 4
     1773566.784       552150.04     1773434.406      552056.724
      1773345.43      551948.217     1773230.412        551687.8
#Sta/Elev= 30
       0  634.82     9.5  634.44      19  635.13    38.1  635.56    57.2  635.35
    76.2  633.18    85.7   631.6    95.3  629.95   104.8  627.02   114.3  622.91
   123.8  617.83   133.4  613.63   142.9  610.67   152.4  609.17     162  608.08
     190  605.57   199.4  603.79   208.7  600.51   218.1  598.32   227.4  597.41
   237.6  598.09   246.2  600.07   264.9   605.3   274.2  606.06   283.6  606.32
   400.4  606.81   488.8  610.62   528.1  611.47   547.7  612.65     587  612.64
#Mann= 3 , 0 , 0
       0     .06       0   218.1    .045       0   237.6     .06       0
Bank Sta=218.1,237.6
XS Rating Curve= 0 ,0
Exp/Cntr=0.3,0.1

Type RM Length L Ch R = 1 ,2992.8  ,26.6,32.6,38
XS GIS Cut Line= 4
       1773660.1      552100.126     1773527.722       552006.81
     1773438.746      551898.303     1773323.728      551637.887
#Sta/Elev= 30
       0  612.74    38.1  610.57    85.7  606.83   104.8  605.67   142.9  604.05
     162  603.58   180.7  602.79     190  602.07   199.4  600.44   208.7  598.03
   218.1  597.16   227.4  597.55   230.9  598.32   236.8  599.62   246.2  602.72
   255.5  604.32   274.2   605.6   283.6  606.38   292.9  607.46   302.3  608.09
   312.1   608.2   341.6  607.77     371  606.42   380.8  606.24   400.4  606.52
   420.1  607.23   449.5  607.79   508.4  610.08   547.7  611.93     587  614.75
#Mann= 3 , 0 , 0
       0     .08       0   208.7    .045       0   230.9     .06       0
Bank Sta=208.7,230.9
XS Rating Curve= 0 ,0
Exp/Cntr=0.3,0.1

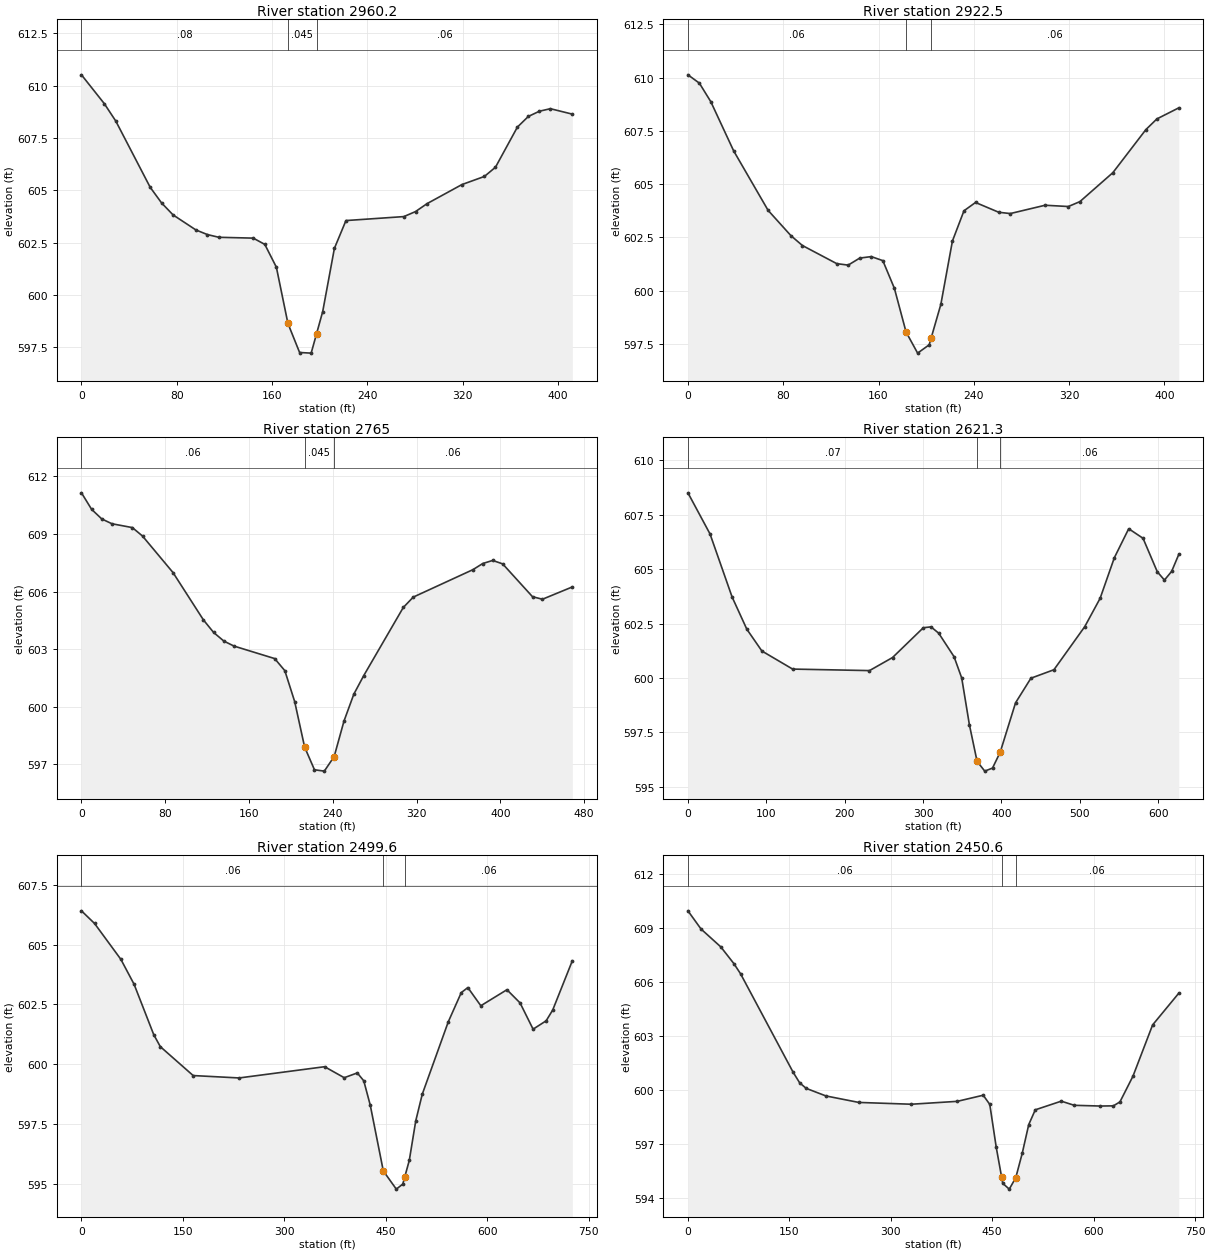
Type RM Length L Ch R = 1 ,2960.2  ,37.8,37.7,37.7
XS GIS Cut Line= 4
     1773647.079       552078.28     1773536.836      551985.398
     1773458.711      551817.864     1773428.329      551740.607
#Sta/Elev= 30
       0  610.52    19.2  609.14    28.8  608.31    57.7  605.14    67.3  604.39
    76.9  603.82    96.1   603.1   105.7  602.88   115.3  602.75   144.2  602.71
   153.9  602.41   163.6  601.32   173.3  598.63   183.1  597.24   192.8  597.21
   197.3  598.13   202.5   599.2   212.3  602.22     222  603.55   270.6  603.74
   280.4  603.98   290.1  604.36   319.3  605.27   338.2  605.66   347.5   606.1
   365.9  608.02   375.1  608.53   384.4  608.78   393.6   608.9     412  608.64
#Mann= 3 , 0 , 0
       0     .08       0   173.3    .045       0   197.3     .06       0
Bank Sta=173.3,197.3
XS Rating Curve= 0 ,0
Exp/Cntr=0.3,0.1

Type RM Length L Ch R = 1 ,2922.5  ,162.3,157.5,152.5
XS GIS Cut Line= 4
     1773685.274      552071.336     1773575.031      551978.454
     1773496.906      551810.919     1773466.524      551733.662
#Sta/Elev= 30
       0  610.13     9.6  609.74    19.2  608.87    38.4  606.56    67.3  603.77
    86.5  602.58    96.1  602.12   124.9  601.27   134.5   601.2   144.2  601.53
   153.9   601.6   163.6  601.41   173.3  600.11   183.1  598.06   192.8  597.07
   202.5  597.46   204.1  597.77   212.3  599.36     222  602.33   231.7  603.75
   241.4  604.14   260.9  603.68   270.6  603.62   299.8  604.01   319.3  603.95
     329  604.18   356.7  605.54   384.4  607.56   393.6  608.06     412  608.58
#Mann= 3 , 0 , 0
       0     .06       0   183.1    .045       0   204.1     .06       0
Bank Sta=183.1,204.1
XS Rating Curve= 0 ,0
Exp/Cntr=0.3,0.1

Type RM Length L Ch R = 1 ,2765    ,137.4,143.7,148.7
XS GIS Cut Line= 4
     1773751.246      552116.475      1773726.94      551923.766
     1773669.649      551849.114     1773596.732      551684.183
#Sta/Elev= 30
       0  611.14     9.7  610.28    19.4  609.78    29.1  609.53    48.6  609.33
    58.3  608.89    87.4  606.99   116.5  604.52   126.2  603.87     136  603.42
   145.7  603.16   184.5  602.51   194.2  601.88   203.6  600.27   213.1   597.9
   222.5  596.72   231.9  596.65   241.3  597.41   250.7  599.26   260.1  600.66
   269.5  601.62   307.3  605.17   316.8  605.71   373.8  607.14   383.2  607.46
   392.7  607.62   402.2  607.44   430.7  605.73   440.2   605.6   468.7  606.24
#Mann= 3 , 0 , 0
       0     .06       0   213.1    .045       0   241.3     .06       0
Bank Sta=213.1,241.3
XS Rating Curve= 0 ,0
Exp/Cntr=0.3,0.1

Type RM Length L Ch R = 1 ,2621.3  ,120.5,121.7,122.4
XS GIS Cut Line= 4
     1773945.473      552139.551      1773931.15      552056.217
     1773728.025       551664.29     1773655.109       551595.28
#Sta/Elev= 30
       0  608.51    28.2  606.62    56.4  603.72    75.2  602.24    94.4  601.24
   133.6  600.41   231.7  600.34   261.1  600.94   300.4  602.31   310.2  602.35
     320  602.06   339.6  600.98   349.4     600   359.2  597.85     369  596.17
   378.8  595.72   388.7  595.86   398.5  596.59   418.1  598.86   437.7  599.99
   467.1  600.38   506.4  602.36     526  603.66   544.2  605.53   562.5  606.86
   580.8  606.42     599  604.88   608.1   604.5   617.3   604.9   626.4  605.68
#Mann= 3 , 0 , 0
       0     .07       0     369    .045       0   398.5     .06       0
Bank Sta=369,398.5
XS Rating Curve= 0 ,0
Exp/Cntr=0.3,0.1

Type RM Length L Ch R = 1 ,2499.6  ,50.9,49,48.6
XS GIS Cut Line= 4
     1774110.621      552081.752     1773893.607      551770.989
     1773810.274      551576.544     1773697.426      551501.891
#Sta/Elev= 30
       0  606.41    19.4  605.88    58.3  604.38    77.8  603.34   106.9  601.23
   116.6  600.73   165.2  599.52   233.2  599.42   359.6  599.89   388.6  599.43
   407.9  599.63   417.5   599.3   427.1  598.28   446.4  595.53   465.6  594.77
   475.2  594.98     478  595.27   484.8  595.97   494.4  597.63     504  598.74
   542.5  601.77   561.7  602.99   571.4   603.2   590.6  602.44   629.2  603.11
   648.6  602.56   667.9  601.46   687.2  601.81   696.9  602.26   725.9  604.32
#Mann= 3 , 0 , 0
       0     .06       0   446.4    .045       0     478     .06       0
Bank Sta=446.4,478
XS Rating Curve= 0 ,0
Exp/Cntr=0.3,0.1

Type RM Length L Ch R = 1 ,2450.6  ,124.7,118.1,111.4
XS GIS Cut Line= 4
     1774150.551      552053.975     1773933.537      551743.211
     1773850.204      551548.766     1773737.357      551474.114
#Sta/Elev= 30
       0  609.93    19.4  608.92    48.6  607.93      68     607    77.8  606.44
   155.5  600.98   165.2  600.39   174.9  600.08   204.1  599.66   252.7   599.3
   330.4   599.2   398.3  599.36   436.7   599.7   446.4  599.19     456   596.8
   463.8  595.18   465.6  594.81   475.2  594.49   484.8  595.12   494.4  596.48
     504  598.07   513.7  598.89   552.1  599.37   571.4  599.14   609.9   599.1
   629.2  599.11   638.9  599.33   658.2  600.76   687.2   603.6   725.9  605.36
#Mann= 3 , 0 , 0
       0     .06       0   463.8    .045       0   484.8     .06       0
Bank Sta=463.8,484.8
XS Rating Curve= 0 ,0
Exp/Cntr=0.3,0.1

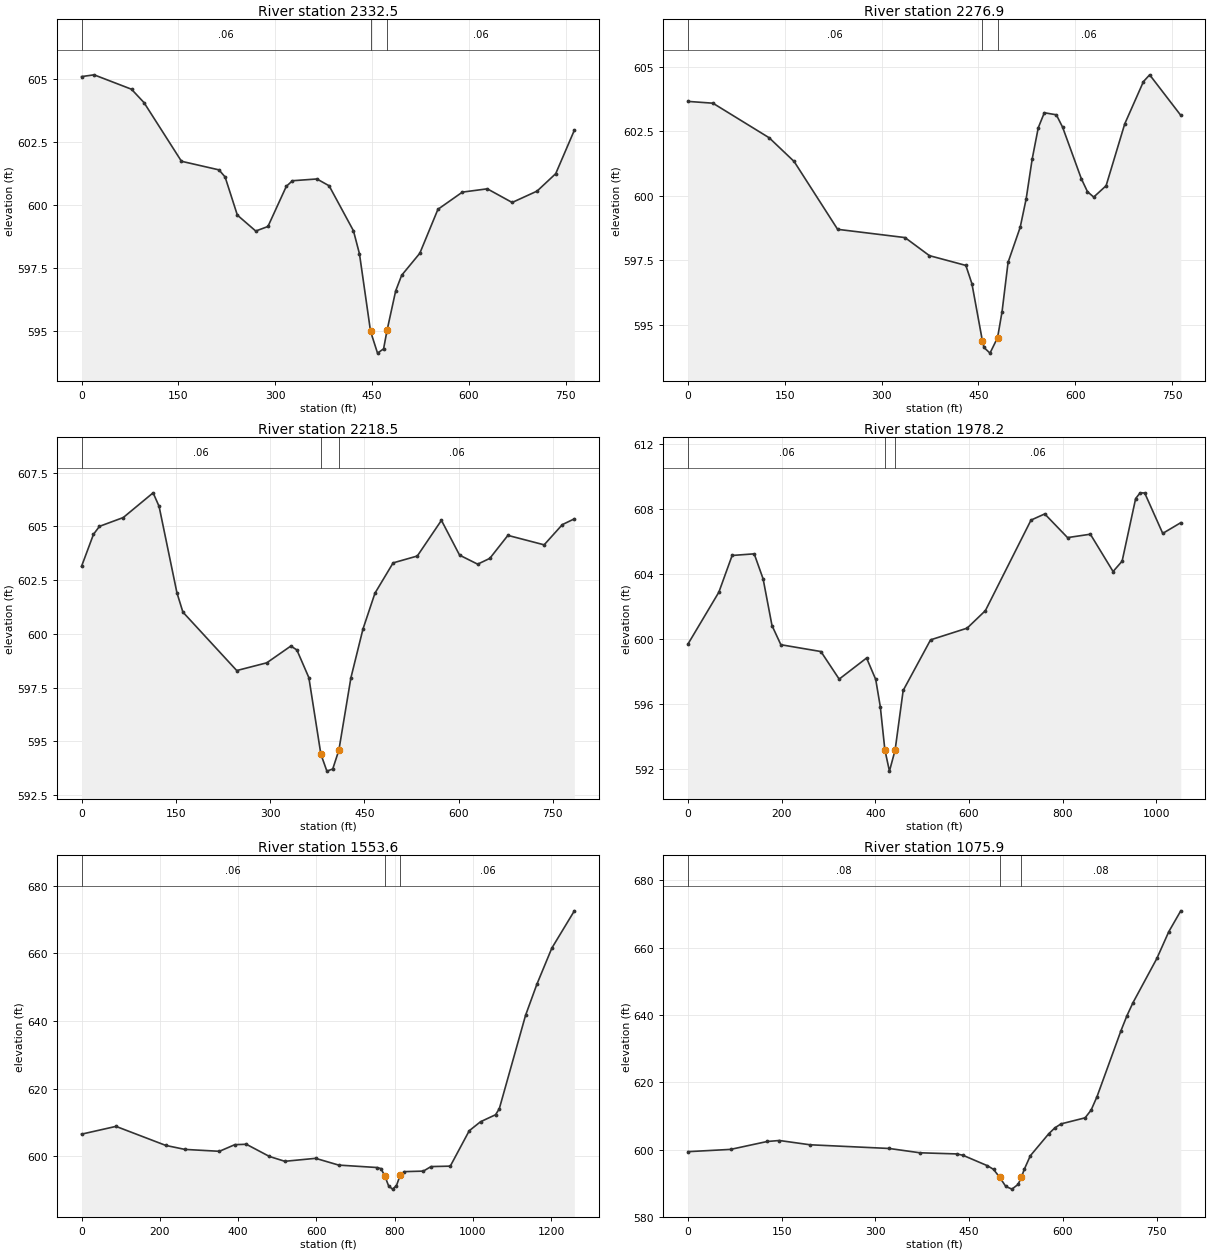
Type RM Length L Ch R = 1 ,2332.5  ,55.6,55.6,55.6
XS GIS Cut Line= 6
      1774218.26      551996.683     1774094.996      551823.072
     1774055.065      551696.336     1774029.024      551635.572
     1773926.593      551514.044      1773789.44      551378.627
#Sta/Elev= 30
       0  605.08    19.4  605.15    77.4  604.58    96.8  604.05   154.8  601.73
   212.9  601.39   222.4  601.11   241.4   599.6   269.9  598.97   288.8  599.15
   317.3  600.74   326.8  600.96   364.7  601.03   383.6  600.76   421.3  598.98
   430.6  598.07   447.8     595   458.6  594.14     468  594.31  473.34  595.04
   486.7   596.6     496  597.22   524.1  598.09   552.2  599.83   590.1  600.51
   628.7  600.64   667.2   600.1   705.8  600.55   734.7  601.24   763.6  602.96
#Mann= 3 , 0 , 0
       0     .06       0   447.8    .045       0  473.34     .06       0
Bank Sta=447.8,473.34
XS Rating Curve= 0 ,0
Exp/Cntr=0.3,0.1

Type RM Length L Ch R = 1 ,2276.9  ,56.7,58.4,60.1
XS GIS Cut Line= 6
     1774270.343      551972.377     1774147.079      551798.766
     1774107.149       551672.03     1774081.107      551611.266
     1773978.676      551489.739     1773841.524      551354.322
#Sta/Elev= 30
       0  603.66    38.7  603.59   125.8  602.25   164.5  601.33   231.9   598.7
   336.3  598.38   374.1  597.68   430.6   597.3     440  596.59  456.33  594.36
   458.6  594.12     468   593.9  479.72   594.5   486.7  595.51     496  597.42
   514.8  598.78   524.1  599.89   533.4  601.43   542.8  602.64   552.2  603.22
   570.8  603.14   580.5  602.66   609.4  600.67     619  600.16   628.7  599.95
   647.9  600.39   676.8  602.79   705.8  604.43   715.4  604.69   763.6  603.12
#Mann= 3 , 0 , 0
       0     .06       0  456.33    .045       0  479.72     .06       0
Bank Sta=456.33,479.72
XS Rating Curve= 0 ,0
Exp/Cntr=0.3,0.1

Type RM Length L Ch R = 1 ,2218.5  ,233.8,240.2,246.5
XS GIS Cut Line= 4
     1774362.357      551812.655     1774199.162      551682.447
     1774053.329      551481.058     1773834.579      551238.002
#Sta/Elev= 30
       0  603.14      19  604.63    28.5     605    66.4  605.41   113.9  606.56
   123.4  605.93   151.8  601.91   161.3  601.01     247  598.29   294.8  598.65
   333.1  599.43   342.7  599.25   361.8  597.96   380.9   594.4   390.5  593.61
   399.8  593.71   409.6  594.59   428.7  597.95   447.9  600.22     467  601.89
   495.9   603.3   534.4  603.62   572.8  605.28   601.7  603.66   630.5  603.24
   649.8  603.51   678.6  604.58   736.3  604.14   765.2  605.08   784.4  605.35
#Mann= 3 , 0 , 0
       0     .06       0   380.9    .045       0   409.6     .06       0
Bank Sta=380.9,409.6
XS Rating Curve= 0 ,0
Exp/Cntr=0.3,0.1

Type RM Length L Ch R = 1 ,1978.2  ,404.4,424.6,444
XS GIS Cut Line= 6
     1774407.496      551833.489     1774348.468      551705.016
     1774348.468      551562.655     1774265.135      551323.072
      1774180.04      550982.692     1774078.937      550853.888
#Sta/Elev= 30
       0  599.68      66  602.88    94.3  605.14   141.4  605.24   160.4   603.7
   179.4  600.82   198.3  599.64   283.8  599.22   322.8  597.52   381.3  598.82
   400.8   597.5   410.6  595.82   420.3  593.17   430.1  591.85  442.16  593.14
   459.4  596.82   517.9  599.94   595.9  600.66   634.9  601.74   732.3  607.32
   761.6   607.7   810.3  606.24     859  606.45   907.5  604.15   926.8  604.79
   955.7  608.65   965.3     609     975  608.99  1013.5   606.5    1052  607.16
#Mann= 3 , 0 , 0
       0     .06       0   420.3    .045       0  442.16     .06       0
Bank Sta=420.3,442.16
XS Rating Curve= 0 ,0
Exp/Cntr=0.3,0.1

Type RM Length L Ch R = 1 ,1553.6  ,475.3,477.8,480.6
XS GIS Cut Line= 4
     1774486.923      552186.353     1774479.009      551863.755
     1774796.385      551309.183     1775015.135      551107.794
#Sta/Elev= 30
       0  606.55      88  608.85   215.1  603.22     264  602.04   352.2  601.48
   391.5  603.44     421  603.56     480  599.95   519.3  598.52   597.9   599.4
   656.9   597.4   755.2  596.68   765.1  596.35   774.9  594.12   784.7  591.18
   794.6  590.29   804.4  591.31   814.2  594.47     824  595.46   873.2  595.62
   892.8  596.96     942  597.09   990.4  607.56  1019.2  610.22  1057.6  612.29
  1067.2  614.07  1134.3   641.7  1163.1  650.86  1201.4  661.58    1259  672.61
#Mann= 3 , 0 , 0
       0     .06       0   774.9    .045       0   814.2     .06       0
Bank Sta=774.9,814.2
XS Rating Curve= 0 ,0
Exp/Cntr=0.3,0.1

Type RM Length L Ch R = 1 ,1075.9  ,578,578.4,575.3
XS GIS Cut Line= 4
     1775001.246      552114.739     1775032.496      551774.461
     1775192.218      551562.655     1775279.024      551402.933
#Sta/Elev= 30
       0  599.38    68.3  600.06   126.9  602.41   146.4   602.7   195.3  601.43
   322.2  600.33   371.2  599.05   430.1  598.71     440  598.32   479.3  595.21
   489.1  594.12   498.9  591.78   508.7  589.05   518.6  588.25   528.4  589.66
  533.57  591.73   538.2  594.09     548  598.17   577.5  604.71   587.3  606.46
   597.2  607.64   635.7  609.44   645.3  611.74   654.8  615.76   693.1  635.34
   702.7  639.81   712.2  643.62   750.5  656.79   769.6  664.75   788.8  670.95
#Mann= 3 , 0 , 0
       0     .08       0   498.9    .045       0  533.57     .08       0
Bank Sta=498.9,533.57
XS Rating Curve= 0 ,0
Exp/Cntr=0.3,0.1

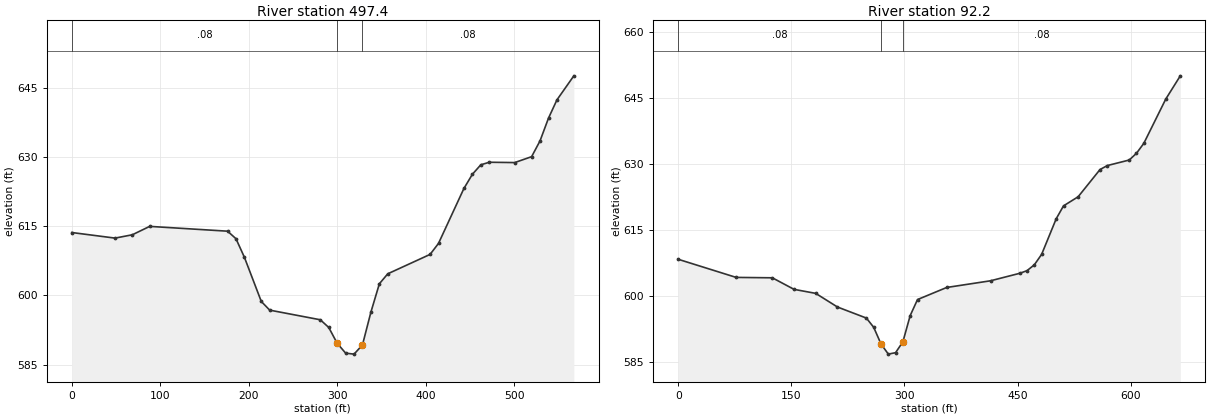
Type RM Length L Ch R = 1 ,497.4   ,426.5,405.2,381.6
XS GIS Cut Line= 4
     1775411.402      552035.746     1775420.083      551859.964
      1775530.76      551716.735     1775558.972      551508.402
#Sta/Elev= 30
       0  613.62    48.9  612.41    68.4  613.13      88  614.95     176  613.91
   185.5  612.28     195  608.27   214.1  598.69   223.6  596.81   280.8  594.72
   290.3  593.06   299.8  589.64   309.4  587.49   318.9  587.28   328.4  589.27
     338  596.42   347.5  602.52     357  604.68   404.8  608.88   414.3  611.26
     443  623.16   452.6  626.24   462.1  628.29   471.7  628.84   500.4  628.77
   519.5  630.05     529  633.47   538.6  638.41   548.1  642.35   567.2  647.56
#Mann= 3 , 0 , 0
       0     .08       0   299.8    .045       0   328.4     .08       0
Bank Sta=299.8,328.4
XS Rating Curve= 0 ,0
Exp/Cntr=0.3,0.1

Type RM Length L Ch R = 1 ,92.2    ,86.7,92.2,97.7
XS GIS Cut Line= 3
     1775700.031      552126.891     1775756.454      551883.836
     1775606.715      551495.381
#Sta/Elev= 30
       0  608.27    76.8  604.15   124.8  604.06   153.6  601.43   182.3  600.52
   211.1  597.42   249.5   594.9   259.2   592.8   268.9  589.01   278.6   586.7
   288.2  587.03   297.9   589.5   307.6  595.47   317.3  599.11     356  601.86
   414.1  603.38   452.8  605.08   462.5  605.68   472.2  607.01   481.9  609.39
   501.2  617.48   510.9  620.42   530.3  622.49   559.3  628.68     569  629.59
   598.1  630.85   607.7  632.39   617.4  634.64   646.5  644.71   665.8     650
#Mann= 3 , 0 , 0
       0     .08       0   268.9    .045       0   297.9     .08       0
Bank Sta=268.9,297.9
XS Rating Curve= 0 ,0
Exp/Cntr=0.3,0.1

Chan Stop Cuts=-1
Use User Specified Reach Order=0
Composite Channel Slope=5